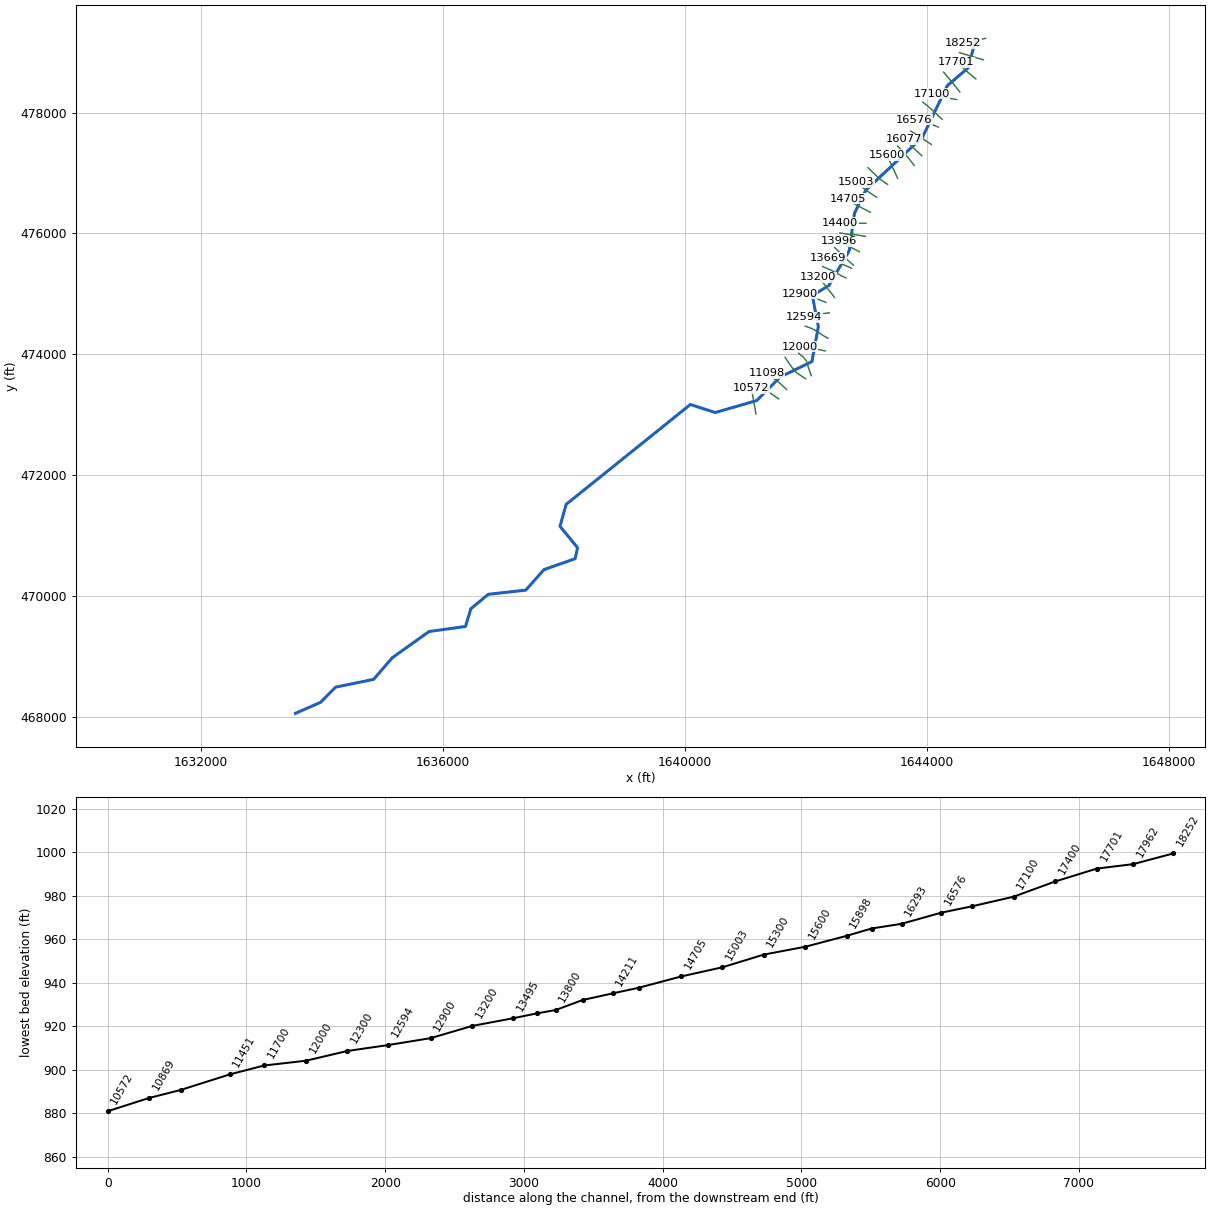
--- UppBwmRn.prj (project) ---

Proj Title=UppBwmRn
Current Plan=p01
Default Exp/Contr=0,0
English Units
Geom File=g01
Flow File=f01
Plan File=p01
BEGIN DESCRIPTION:
---------- MODELED AS PART OF WVEM CTP PROGRAM, 2025----------
Stream Name: Upper Bowman Run
Flood Zone: AFH
Marshall County, WV
HEC-RAS Version: RAS 6.6
Vertical Datum: NAVD88
Projection: NAD 1983 StatePlane West Virginia N FIPS 4701 (US Feet)
Terrain: 1-meter West Virginia FEMA R3 South Central (collected 2018-2019)
Land Use: 2024 NLCD
Hydrologic Method:
Duda et al., "Estimation of magnitude and frequency of floods for rural, unregulated streams in and near Virginia and West Virginia." September 8, 2025.
Additional Model Notes:
None
END DESCRIPTION:
DSS Export Rating Curves= 0
DSS Export Rating Curve Sorted= 0
DSS Export Volume Flow Curves= 0
DXF OffsetX= 0
DXF OffsetY= 0
DXF ScaleX= 0
DXF ScaleY= 0

--- UppBwmRn.p01 (plan) ---

Plan Title=Floodplain
Program Version=6.60
Short Identifier=Floodplain
Geom File=g01
Flow File=f01
Subcritical Flow
K Sum by GR= 0
Std Step Tol= 0.01
Critical Tol= 0.01
Num of Std Step Trials= 20
Max Error Tol= 0.3
Flow Tol Ratio= 0.001
Split Flow NTrial= 30
Split Flow Tol= 0.02
Split Flow Ratio= 0.02
Log Output Level= 0
Friction Slope Method= 1
Unsteady Friction Slope Method= 2
Unsteady Bridges Friction Slope Method= 1
Parabolic Critical Depth
Global Vel Dist= 0 , 0 , 0
Global Log Level= 0
CheckData=False
Encroach Param=-1 ,0,0, 0
Flow Ratio Tolerance=0.1
Flow Ratio Min Ratio=0.5
Flow Ratio Max Ratio=4
Flow Ratio Max Iterations= 10
Mapping Interval=1HOUR
Computation Time Step Use Courant=        0
Computation Time Step Use Time Series=    0
Computation Time Step Count To Double=0
Computation Time Step Max Doubling=0
Computation Time Step Max Halving=0
Computation Time Step Residence Courant=0
Run HTab= 0
Run UNet= 0
Run Sediment= 0
Run PostProcess= 0
Run WQNet= 0
Run RASMapper=-1
UNET Theta= 0
UNET Theta Warmup= 0
UNET ZTol= 0
UNET ZSATol= 0
UNET MxIter= 0
UNET Max Iter WO Improvement= 0
UNET MaxInSteps= 0
UNET DtIC= 0
UNET DtMin= 0
UNET MaxCRTS= 0
UNET WFStab= 0
UNET SFStab= 0
UNET WFX= 1
UNET SFX= 1
UNET Gravity=32.17405
UNET 1D Methodology=Finite Difference
UNET DSS MLevel= 1
UNET Pardiso=0
UNET DZMax Abort= 0
UNET Use Existing IB Tables= 0
UNET Froude Reduction=False
UNET Froude Limit= 0
UNET Froude Power= 0
UNET D1 Cores= 0
UNET WindReference=Eulerian
UNET WindDragFormulation=Hsu (1988)
UNET D2 Coriolis=0
UNET D2 Cores= 0
UNET D2 Theta= 1
UNET D2 Theta Warmup= 1
UNET D2 Z Tol= 0.01
UNET D2 Volume Tol= 0.01
UNET D2 Max Iterations= 20
UNET D2 Advanced Convergence=0
UNET D2 WS Max Tol=0.15
UNET D2 WS RMS Tol=0.002
UNET D2 WS Stall Tol=1
UNET D2 Equation= 0
UNET D2 RampUpFraction=0.1
UNET D2 TimeSlices= 1
UNET D2 Turbulence Formulation=Non-Conservative (original)
UNET D2 Eddy Viscosity=0.3
UNET D2 Transverse Eddy Viscosity=0.1
UNET D2 Smagorinsky Mixing=0
UNET D2 BCVolumeCheck=0
UNET D2 Cores=0
UNET D2 SolverType=PARDISO (Direct)
UNET D2 Minimum Iterations= 3
UNET D2 Maximum Iterations= 30
UNET D2 Restart Number= 10
UNET D2 Relaxation Coeff=1.3
UNET D2 SOR Precondition Iterations= 10
UNET D2 ILUT Maximum Fill= 8
UNET D2 ILUT Tolerance=1E-08
UNET D2 Convergence Tolerance=0.00001
PS Theta= 1
PS WS Tol= 0.01
PS Volume Tol= 0.01
PS Max Iterations= 20
PS Equation= 0
PS Advance Time Step=-1
PS Target Courant=0.9
PS Time Slices= 1
PS Iterate With 2D=0
PS Project Initial WSE from DS=-1
PS Ramp Up Initial WSE from US=-1
PS Cores=0
UNET D1D2 MaxIter= 0
UNET D1D2 ZTol=0.01
UNET D1D2 QTol=0.1
UNET D1D2 MinQTol=1
Write IC File= 0
Write IC File at Fixed DateTime=0
Write IC File at Sim End=0
Echo Input=False
Echo Parameters=False
Echo Output=False
Write Detailed= 0
HDF Write Warmup=0
HDF Write Time Slices=0
HDF Flush=0
HDF Compression= 1
HDF Chunk Size= 1
HDF Spatial Parts= 1
HDF Use Max Rows=0
HDF Fixed Rows= 1
Calibration Method= 0
Calibration Iterations= 20
Calibration Max Change=0.05
Calibration Tolerance=0.2
Calibration Maximum=1.5
Calibration Minimum=0.5
Calibration Optimization Method= 1
WQ AD Non Conservative
WQ ULTIMATE=-1
WQ Max Comp Step=1HOUR
WQ Output Interval=15MIN
WQ Output Selected Increments= 0
WQ Create Restart=0
WQ Fixed Restart=0
WQ System Summary=0
WQ Write To DSS=0
Sorting and Armoring Iterations= 10
XS Update Threshold= 0.02
Bed Roughness Predictor= 0
Processes Affected by Predictor=Sediment Only
Hydraulics Update Threshold= 0.02
Energy Slope Method= 1
Volume Change Method= 1
Sediment Retention Method= 0
Sediment TS Multiplier= 1
Warm Up Method= 0
XS Weighting Method= 0
Number of US Weighted Cross Sections= 1
Number of DS Weighted Cross Sections= 1
Upstream XS Weight=0
Main XS Weight=1
Downstream XS Weight=0
Number of DS XS's Weighted with US Boundary= 1
Upstream Boundary Weight= 1
Weight of XSs Associated with US Boundary= 0
Number of US XS's Weighted with DS Boundary= 1
Downstream Boundary Weight= 0.5
Weight of XSs Associated with DS Boundary= 0.5
Percentile Method= 0
Sediment Output Level= 3
Mass or Volume Output= 0
Output Increment Type= 1
Profile and TS Output Increment= 1
Transport Output Increment 1
XS Output Flag= 0
XS Output Increment= 10
Read HDF5 Sediment Hotstart= 0
Sediment Hotstart Type= 0
Write Gradation File= 0
Read Gradation Hotstart= 0
Write HDF5 File= 1
Write Binary Output= 1
Write DSS Sediment File= 0
DSS Sediment Output Type= 1
SV Curve= 0
Specific Gage Flag= 0
Subcell Erosion Methods= 0
Subcell Deposition Methods= 0
Advection Scheme= 1
Matrix Solver= 0
Implicit Weighting Factor= 1
Maximum Outer Loop Convergence Iterations= 5
Convergence Maximum Absolute= 0.001
Convergence RMSE= 0.0001
Grain Fractions Max Abs Error= 0.001
Max Subgrid Regions= 1
Max Subgrid Length Scale= 3.402823E+38
Initial Layer Thickness= 3
Min Layer Thickness= 0.1
Max Layer Thickness= 6
Number of Layers= 5

--- UppBwmRn.f01 (steady flow) ---

Flow Title=Flow
Program Version=6.60
Number of Profiles= 1
Profile Names=P100yr
River Rch & RM=UppBwmRn,Main,18252
     845
River Rch & RM=UppBwmRn,Main,15003
    1060
River Rch & RM=UppBwmRn,Main,14705
    1330
River Rch & RM=UppBwmRn,Main,9349
    1460
River Rch & RM=UppBwmRn,Main,7200
    1650
Boundary for River Rch & Prof#=UppBwmRn,Main            , 1
Up Type= 0
Dn Type= 3
Dn Slope=0.020596
DSS Import GetInterval= 0
DSS Import GetPeak= 0
DSS Import FillOption= 0

--- UppBwmRn.g01 (geometry) ---

Geom Title=Geometry
Program Version=6.60

River Reach=UppBwmRn        ,Main
Reach XY= 30
     1644808.385      479211.647     1644681.044      478736.935
     1644337.216      478444.115     1643929.723       477595.88
     1642988.466      476713.262     1642803.552      476334.559
     1642716.483      475714.248     1642382.216      475140.582
     1642106.356       474971.12      1642205.79      474460.798
     1642099.175      473879.657     1641577.447      473627.088
     1641186.708      473235.607     1640500.767       473037.42
     1640090.856      473170.483     1638037.223      471518.529
     1637935.547      471155.519     1638225.871      470800.492
     1638184.276      470619.407      1637671.81      470440.155
     1637369.054      470100.076     1636749.373      470030.816
     1636460.602       469790.42     1636373.076       469499.22
      1635771.17      469415.239     1635162.609      468981.344
     1634854.575      468623.671     1634226.106      468495.304
     1633977.479       468243.85     1633561.414      468061.378

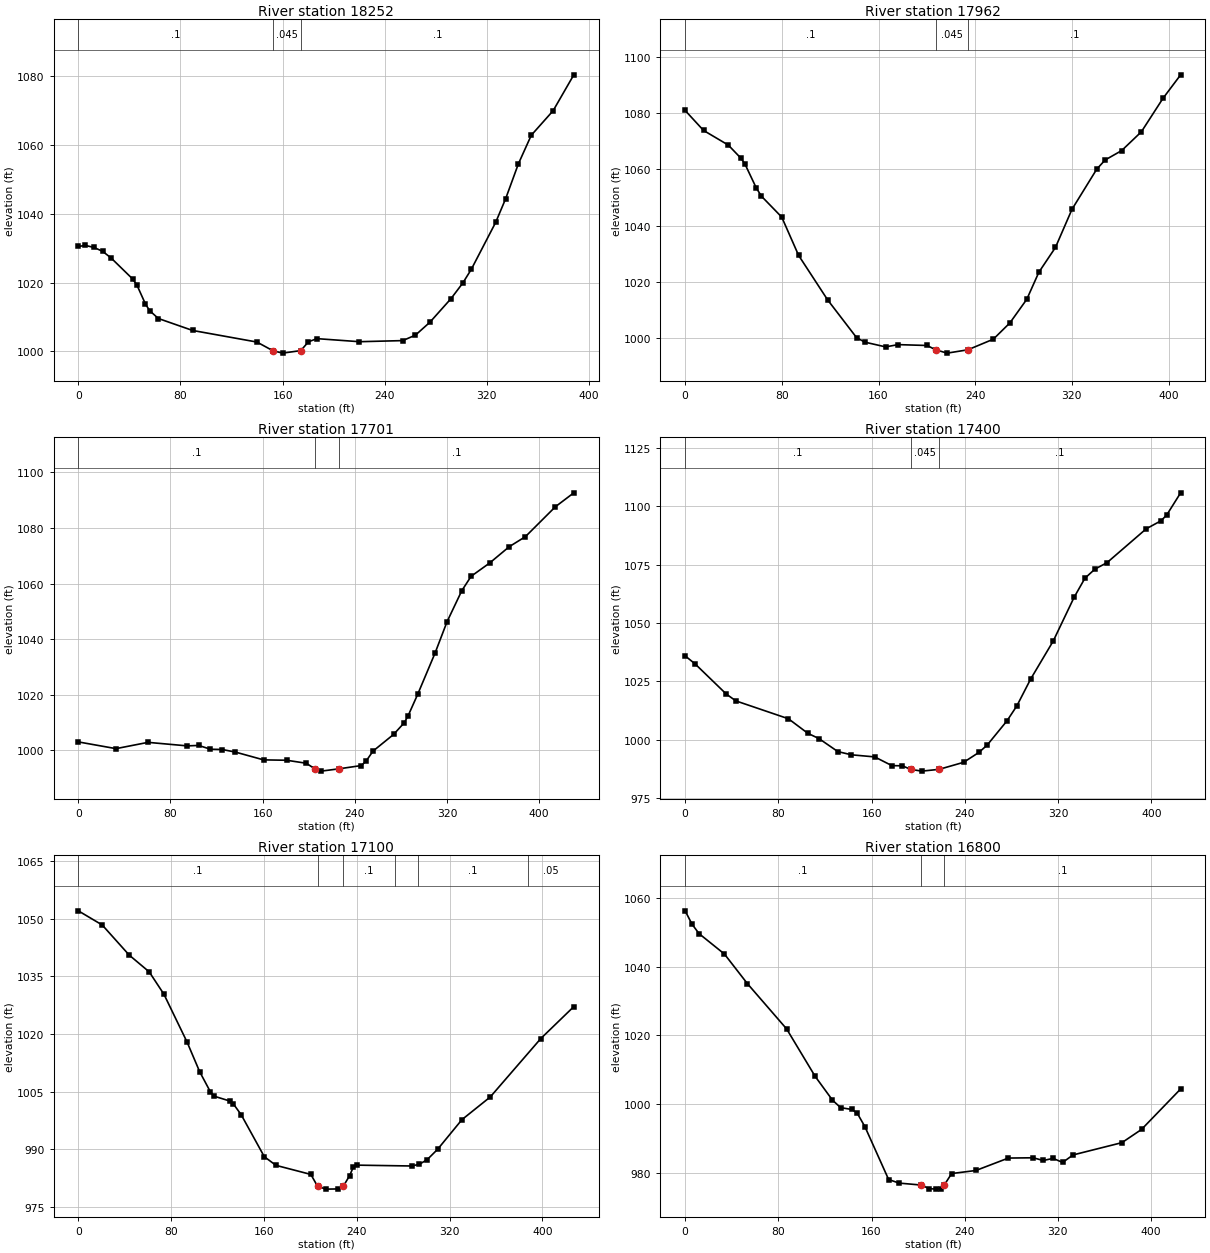
Type RM Length L Ch R = 1 ,18252   ,294.5,290.5,283.4
XS GIS Cut Line= 2
1644971.94065739479227.0340729851644592.74804256479144.363250652
#Sta/Elev= 30
       0  1030.5     5.6 1030.81    12.3 1030.21      19  1029.1    25.7 1027.15
    42.5 1021.08    45.9 1019.29    52.6 1013.77    55.9 1011.84    62.7 1009.57
    89.5  1006.1   139.9 1002.73  152.241000.245     160  999.51  174.281000.247
   180.2 1002.79   186.9 1003.72   220.2 1002.83   254.1 1003.15   264.1 1004.75
   275.4 1008.49   291.9 1015.34   301.1 1019.85   307.8 1023.85   326.9  1037.5
   334.7 1044.36   344.7 1054.52   354.8 1062.83   371.9 1069.95   388.1 1080.38
#Mann= 3 ,-1,0
       0      .1       0  152.24    .045       0  174.28      .1       0
Bank Sta=152.24,174.28
XS Rating Curve= 0 ,0
Exp/Cntr(USF)=0,0
Exp/Cntr=0.3,0.1

Type RM Length L Ch R = 1 ,17962   ,263.6,260.9,254.8
XS GIS Cut Line= 2
1644931.78509954478872.2893664871644539.18020644478990.385283277
#Sta/Elev= 30
       0 1081.02    15.2 1073.92    35.7  1068.7      46 1064.09    49.4 1062.02
    58.8 1053.47    63.1 1050.49    79.9 1043.05    93.9 1029.38   117.9 1013.54
   141.9 1000.06   148.8  998.47   165.9  996.79   176.2   997.6   200.2  997.29
   207.3995.7563   216.8  994.57  233.94995.7559     255  999.54   268.7 1005.33
   282.7 1013.76   292.7 1023.41   306.4 1032.22   320.1 1045.82   340.6 1060.13
   347.5 1063.38   361.2 1066.74   377.5 1073.43   395.4 1085.36     410 1093.73
#Mann= 3 ,-1,0
       0      .1       0   207.3    .045       0  233.94      .1       0
Bank Sta=207.3,233.94
XS Rating Curve= 0 ,0
Exp/Cntr(USF)=0,0
Exp/Cntr=0.3,0.1

Type RM Length L Ch R = 1 ,17701   ,301.9,301.1,298.6
XS GIS Cut Line= 6
1644809.53767668478555.7915457491644742.31897908478611.808494091
 1644684.7026245478659.8228337621644609.24345784478725.476901919
1644556.13135934478778.8954302521644480.94089292478832.228656918
#Sta/Elev= 30
       0 1003.04    32.7 1000.62    60.5 1002.88    94.6 1001.61   104.4 1001.78
   114.7 1000.41   124.9 1000.31   136.4  999.37   160.8  996.58   180.8  996.44
   197.8  995.37  205.29993.3585   210.8  992.53  226.13993.3566   245.7  994.54
     250   996.3   255.8  999.75   273.6 1005.73   282.9 1009.95   286.3 1012.54
   294.5 1020.14   309.6 1035.01     320 1046.28   332.8 1057.45   340.9 1062.63
     357 1067.41     374 1073.28     388 1076.88     414 1087.63     430 1092.65
#Mann= 3 ,-1,0
       0      .1       0  205.29    .045       0  226.13      .1       0
Bank Sta=205.29,226.13
XS Rating Curve= 0 ,0
Exp/Cntr(USF)=0,0
Exp/Cntr=0.3,0.1

Type RM Length L Ch R = 1 ,17400   ,289.6,300,305.9
XS GIS Cut Line= 6
1644545.31609225478339.0291839991644491.41626567478408.011985675
1644444.50166135478466.544677004 1644380.4827605478543.366373762
1644332.46874893478600.9827283321644276.47771917478668.223079428
#Sta/Elev= 30
       0 1035.92     8.7  1032.4    35.2 1019.61    43.5 1016.65    88.6    1009
   105.3 1002.76   114.8 1000.52     131  994.95   142.7  993.57   162.6  992.68
   177.4  988.94   186.4  988.87   193.4987.3443     203  986.59  217.83987.3444
   238.9  990.36   252.2  994.65   259.2  997.79   276.1  1008.1   284.6 1014.53
   296.4 1025.98   315.8 1042.28   333.7 1060.98     343 1069.16   351.6 1073.06
   361.9 1075.79   395.6  1090.3   408.3 1093.74   413.2 1096.24   425.1 1105.69
#Mann= 3 ,-1,0
       0      .1       0   193.4    .045       0  217.83      .1       0
Bank Sta=193.4,217.83
XS Rating Curve= 0 ,0
Exp/Cntr(USF)=0,0
Exp/Cntr=0.3,0.1

Type RM Length L Ch R = 1 ,17100   ,303,300.1,290.1
XS GIS Cut Line= 6
1644491.41987459478215.0993137511644405.06506042478229.356503084
1644331.11802985478241.9555592541644232.85904001478260.534590334
1644159.16627401478274.476819679 1644076.5345495478308.676226333
#Sta/Elev= 30
       0 1052.11    20.6 1048.42    43.9 1040.56    61.1  1036.2    73.8 1030.36
    93.8 1017.85   104.6 1010.16   113.7    1005   117.1 1003.79   130.4 1002.55
   133.7 1001.75   140.4  998.94   160.3  988.02   170.3  985.77   200.4   983.4
  206.27980.2572   213.7  979.57   223.8  979.62  228.26980.2556   233.8  983.09
   237.1  985.38   240.5  985.82   287.3   985.6   293.9  986.05   300.6  987.24
   309.6  989.94   330.6  997.68     355 1003.59   398.6 1018.83     427 1027.14
#Mann= 6 ,-1,0
       0      .1       0  206.27    .045       0  228.26      .1       0
  272.54     .05       0  292.54      .1       0  387.54     .05       0
Bank Sta=206.27,228.26
XS Rating Curve= 0 ,0
Exp/Cntr(USF)=0,0
Exp/Cntr=0.3,0.1

Type RM Length L Ch R = 1 ,16800   ,219.2,223.4,226.7
XS GIS Cut Line= 6
1644251.43643068477889.5333638341644186.79745235477948.525699928
1644132.22899193477999.9773686681644059.37972817478068.482809082
  1644001.603597478116.5325817611643932.93247451478171.128929257
#Sta/Elev= 30
       0 1056.39     5.8 1052.54    11.9 1049.74    33.7 1043.78    53.5 1035.11
    87.1 1021.92   111.6 1008.07   126.5 1001.12   133.5  998.93   143.2   998.4
   147.7  997.34   154.4  993.33   174.7  977.95   183.7  976.91   202.7976.3392
   209.4   975.3   215.3  975.15   219.4  975.31  222.44976.3389   228.8   979.7
   249.6  980.59   277.5  984.22   298.8   984.3   307.4  983.51   315.9  984.12
   324.1  982.94     333  985.13     375  988.72   391.8  992.57   425.4 1004.39
#Mann= 3 ,-1,0
       0      .1       0   202.7    .045       0  222.44      .1       0
Bank Sta=202.7,222.44
XS Rating Curve= 0 ,0
Exp/Cntr(USF)=0,0
Exp/Cntr=0.3,0.1

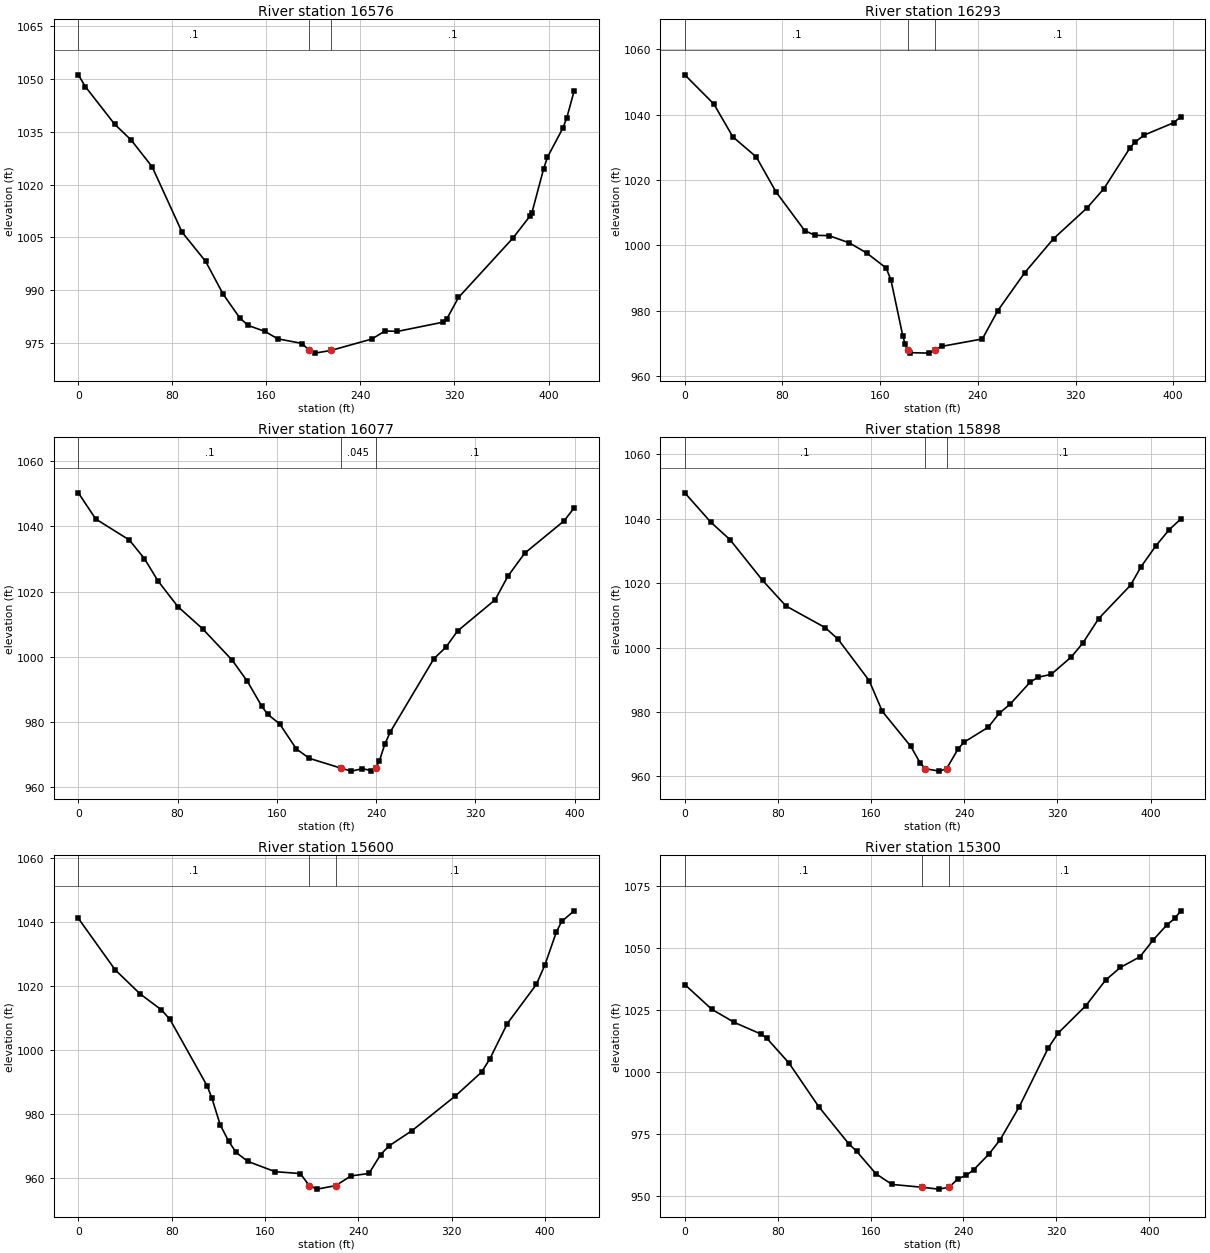
Type RM Length L Ch R = 1 ,16576   ,284.4,283,279.3
XS GIS Cut Line= 4
1644191.09083394477758.0637203361644032.39257377477824.426199642
1643903.11869259 477874.534674611643792.30077927477882.471928123
#Sta/Elev= 30
       0 1051.13     5.9 1047.81    30.8 1037.16      45 1032.61    62.8 1025.04
    88.2 1006.52   108.3  998.21   123.2  988.91   137.5   982.1   144.6  980.03
   158.8  978.34   169.5  976.26   190.6  974.92  196.16  972.96   201.4  972.19
  214.98  972.96   249.6  976.18     261  978.49   271.5  978.35   310.2  980.97
   313.6  981.98   323.4  987.97   369.5 1004.74   384.6 1011.22   385.9 1012.05
   395.8 1024.43   399.1 1027.78   412.2 1036.01   415.5  1038.9   421.8 1046.57
#Mann= 3 ,-1,0
       0      .1       0  196.16    .045       0  214.98      .1       0
Bank Sta=196.16,214.98
XS Rating Curve= 0 ,0
Exp/Cntr(USF)=0,0
Exp/Cntr=0.3,0.1

Type RM Length L Ch R = 1 ,16293   ,217.4,216.8,214
XS GIS Cut Line= 2
1644074.32221512477471.869998194 1643734.3779374477694.021475962
#Sta/Elev= 30
       0 1052.13    23.8 1043.21    39.4 1033.16    58.5 1027.07    74.7 1016.37
    98.2 1004.54   106.5 1003.11   118.1    1003   134.7  1000.8   148.9  997.72
   164.9  993.12   168.8  989.54   178.5  972.47   180.5  969.76  182.82 968.125
   184.5  967.25   200.1  967.11  205.12 968.128   210.5  969.18   243.7  971.44
   256.4  980.11   278.5  991.72     302 1002.07   329.5 1011.48   343.3 1017.37
   364.7 1029.86   368.7 1031.57   376.5 1033.76   400.4 1037.49   406.1 1039.28
#Mann= 3 ,-1,0
       0      .1       0  182.82    .045       0  205.12      .1       0
Bank Sta=182.82,205.12
XS Rating Curve= 0 ,0
Exp/Cntr(USF)=0,0
Exp/Cntr=0.3,0.1

Type RM Length L Ch R = 1 ,16077   ,177.2,178.5,177
XS GIS Cut Line= 2
1643915.94823251477284.3386401591643625.19593726477558.389759186
#Sta/Elev= 30
       0 1050.31      14 1042.29    41.1 1035.84    53.2 1030.15    64.3 1023.23
    80.2 1015.41   100.1 1008.62     124  998.97   136.3  992.45   147.9   984.8
   152.7  982.33   162.2  979.46   175.7  971.75   186.2  968.86  211.36  965.89
     220  964.94     229  965.68   236.1  965.11   239.5965.8895   242.5  967.91
     247  973.21   251.5  977.02   286.6  999.45   296.2 1002.94   305.6 1007.92
   335.9  1017.5   346.2 1024.74   359.7 1031.77   391.6 1041.75   399.6 1045.69
#Mann= 3 ,-1,0
       0      .1       0  211.36    .045       0   239.5      .1       0
Bank Sta=211.36,239.5
XS Rating Curve= 0 ,0
Exp/Cntr(USF)=0,0
Exp/Cntr=0.3,0.1

Type RM Length L Ch R = 1 ,15898   ,302.2,298.2,295.9
XS GIS Cut Line= 6
1643791.22442459477123.8898819981643737.21206543477192.729967415
 1643690.9155701477251.7350987491643626.39929493477328.221822426
1643574.68679993477382.9776184261643513.57832634477446.249801591
#Sta/Elev= 30
       0 1048.07    22.4 1038.92    38.8 1033.52    66.8 1020.86    86.8 1012.93
   120.6 1006.18   131.7 1002.54   158.3  989.74   169.6  980.17   194.1  969.27
   202.2  964.07  206.57962.3435   218.5  961.59  224.82 962.346   234.8  968.55
   239.8  970.58   260.6  975.24   269.9  979.52   279.5  982.44   296.6  989.24
   303.3  990.77   314.6  991.65     332   997.1   341.7 1001.31   355.4 1008.98
   382.8 1019.37   391.9 1025.15   404.3 1031.48   415.9 1036.59   425.8 1039.88
#Mann= 3 ,-1,0
       0      .1       0  206.57    .045       0  224.82      .1       0
Bank Sta=206.57,224.82
XS Rating Curve= 0 ,0
Exp/Cntr(USF)=0,0
Exp/Cntr=0.3,0.1

Type RM Length L Ch R = 1 ,15600   ,295.3,299.9,304
XS GIS Cut Line= 6
1643516.69052485476911.2124858351643480.02294725476990.658849254
1643448.59322008477058.7558259221643406.68746401477149.551576093
1643375.25740875477217.6482246671643338.58983117477297.094916165
#Sta/Elev= 30
       0 1041.07    31.5 1025.03    52.9  1017.5    71.2 1012.51    78.5 1009.55
   110.4  988.79   114.4  985.05   121.6  976.65   128.8  971.51   135.3     968
   145.2  965.23   168.6  962.01   190.2  961.42  197.99957.6569   204.7  956.56
  220.66957.6573   233.6  960.67   249.1  961.45   259.1  967.32   266.1     970
   286.2  974.85   323.2  985.64   345.6  993.05   352.7  997.18   367.7 1008.23
   392.6 1020.44   399.9  1026.5   409.8 1036.84   414.3 1040.09     425 1043.41
#Mann= 3 ,-1,0
       0      .1       0  197.99    .045       0  220.66      .1       0
Bank Sta=197.99,220.66
XS Rating Curve= 0 ,0
Exp/Cntr(USF)=0,0
Exp/Cntr=0.3,0.1

Type RM Length L Ch R = 1 ,15300   ,293.8,297.5,297.8
XS GIS Cut Line= 6
1643350.91329734476810.6743010881643277.27105618476860.418624178
1643216.54479967476905.4421561661643144.24048235476974.522398591
1643090.06736234 477026.390077011643026.86506093477086.902423173
#Sta/Elev= 30
       0 1035.21    23.3 1025.24    42.7 1019.97    65.6 1015.31    70.6 1013.61
    89.6 1003.71   115.3  986.13   141.1  971.22   148.1   968.1   164.5  959.16
   178.4  954.83  204.25953.6941   218.6  952.94  227.63953.6929   235.3  957.13
   242.4  958.49   248.9  960.77     262  967.07   271.6  972.81   288.1  986.12
     313 1009.72   321.6 1015.73   345.5 1026.77   362.4    1037   375.2 1042.12
   391.9 1046.35   403.5  1053.2   415.1 1059.19   422.1 1061.86     427 1064.86
#Mann= 3 ,-1,0
       0      .1       0  204.25    .045       0  227.63      .1       0
Bank Sta=204.25,227.63
XS Rating Curve= 0 ,0
Exp/Cntr(USF)=0,0
Exp/Cntr=0.3,0.1

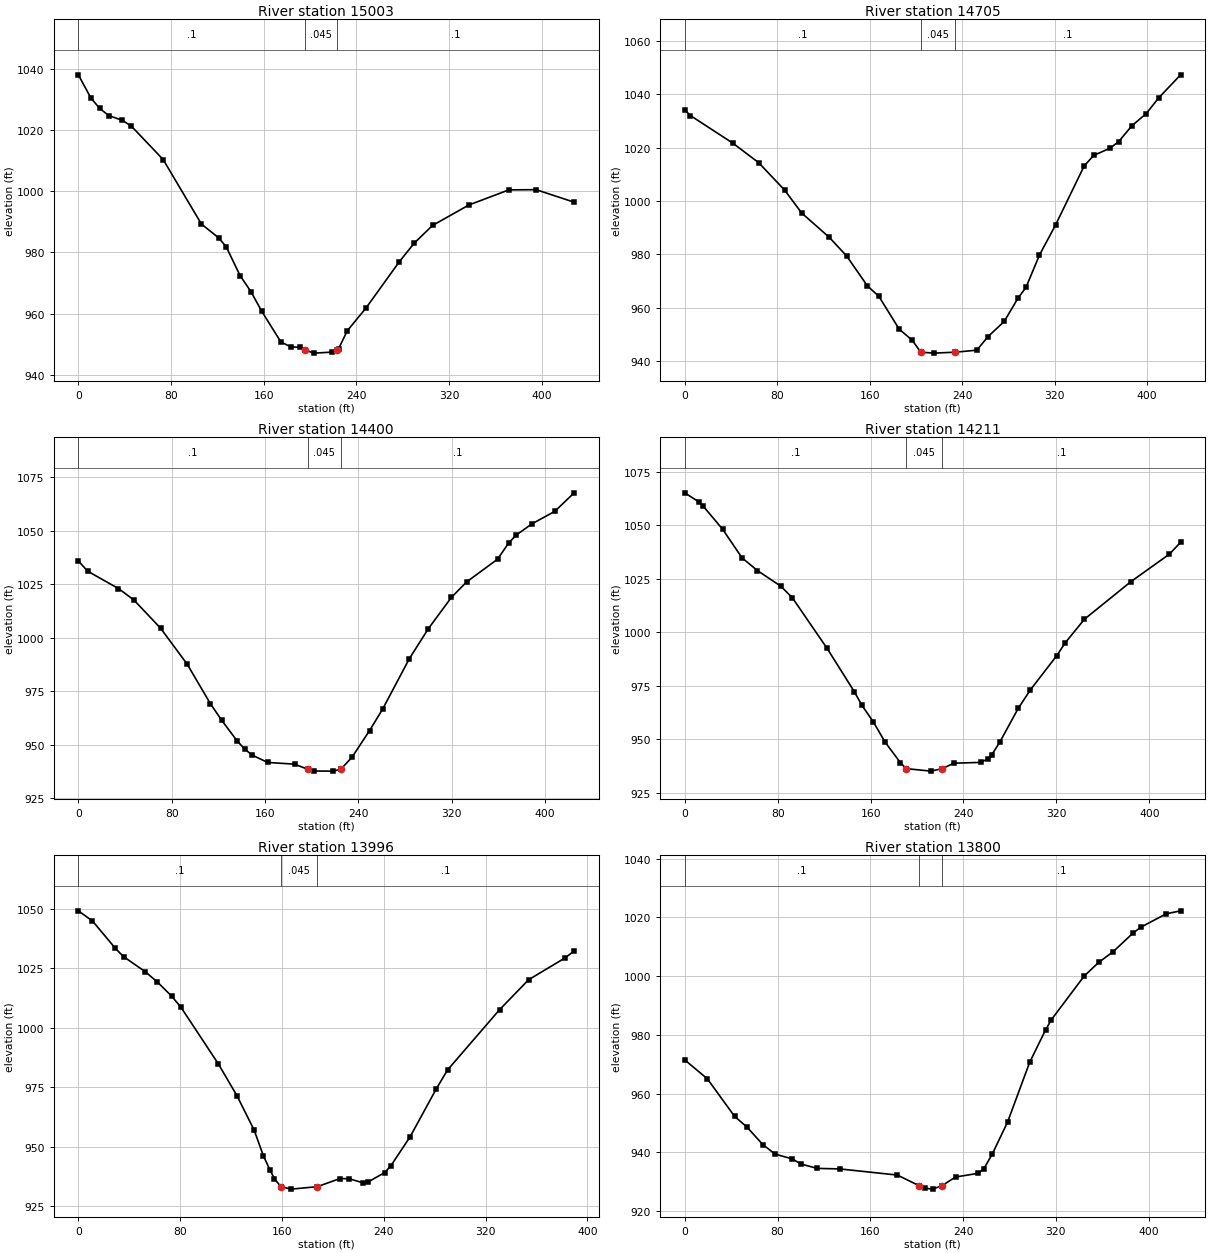
Type RM Length L Ch R = 1 ,15003   ,293,297.7,296.4
XS GIS Cut Line= 6
1643171.16365685476598.560224012   1643095.81407476646.358684838
1643032.51268743  476688.24311551642951.39670792476746.950019091
1642892.97129984476793.9761717621642824.80805033476848.840235248
#Sta/Elev= 30
       0 1037.97    10.8 1030.43    18.4 1027.01    26.3 1024.66      38 1023.11
    45.8  1021.2    73.2  1010.3   106.2  989.25   121.2  984.71   127.6  981.81
   139.6   972.4   148.9   967.2   158.3  960.73   174.8  950.74   183.4  949.15
   191.3     949  195.59948.0622   203.7  947.11   218.9  947.44  223.14948.0629
   224.5   948.5     232  954.39   248.2  961.84     277  976.98   289.9  983.05
   305.6  988.79     337  995.48   371.5 1000.41     395 1000.47   427.8  996.39
#Mann= 3 ,-1,0
       0      .1       0  195.59    .045       0  223.14      .1       0
Bank Sta=195.59,223.14
XS Rating Curve= 0 ,0
Exp/Cntr(USF)=0,0
Exp/Cntr=0.3,0.1

Type RM Length L Ch R = 1 ,14705   ,297.7,304.9,311.4
XS GIS Cut Line= 6
1643063.75967218476349.2122974991642987.03935318476391.776844919
 1642919.5056956476424.615033835 1642831.1357936476472.430555001
1642769.34949984 476517.880923421642698.87654367476572.053387254
#Sta/Elev= 30
       0  1034.2     4.8 1032.09    41.4 1021.76    63.9 1014.39    86.4 1004.06
   101.1  995.49   125.1   986.3   140.1  979.29     158   968.1   167.8  964.25
   185.5  951.85   196.7  947.74   204.1  943.24   215.3  942.88     234  943.23
   252.6  943.99   262.2  949.04   276.3  954.78   288.3  963.58   295.1  967.53
   306.8  979.71   320.9  991.15   345.4  1013.1   353.7 1017.12   367.7 1019.79
   375.2 1022.25   386.8 1028.27   399.2 1032.84   409.8 1038.66   428.9 1047.37
#Mann= 3 ,-1,0
       0      .1       0   204.1    .045       0     234      .1       0
Bank Sta=204.1,234
XS Rating Curve= 0 ,0
Exp/Cntr(USF)=0,0
Exp/Cntr=0.3,0.1

Type RM Length L Ch R = 1 ,14400   ,189.4,189.4,189.4
XS GIS Cut Line= 6
1642993.00751708476167.3278187511642905.51458184476168.451504171
1642830.52096543476169.4131164251642730.52903943476170.696578428
1642655.53542301 476171.658846841642568.04248776476172.781548008
#Sta/Elev= 30
       0 1035.94     8.1 1031.11    34.4 1023.04    47.5 1017.76    70.5  1004.5
    93.4  987.59   113.1  969.29     123  961.37   136.1  951.82   142.6  947.98
   149.2  945.12   162.3  941.75   185.3  940.95  196.73938.5558   201.7  937.73
   218.1  937.69  224.95938.5583   234.5  944.12   249.6  956.62   260.8  966.65
   283.7  990.24   300.1 1004.34   319.8 1018.91   332.9 1026.16   359.3 1036.74
     369 1044.43   375.3 1048.01   388.7 1053.24   408.4 1059.12     425 1067.78
#Mann= 3 ,-1,0
       0      .1       0  196.73    .045       0  224.95      .1       0
Bank Sta=196.73,224.95
XS Rating Curve= 0 ,0
Exp/Cntr(USF)=0,0
Exp/Cntr=0.3,0.1

Type RM Length L Ch R = 1 ,14211   ,220.5,214.4,206.9
XS GIS Cut Line= 5
1642984.27731514475950.6258676461642810.71375799475980.541329798
 1642722.2524307475981.6335985221642648.28440278475993.845844433
1642561.99422104 476008.09220703
#Sta/Elev= 30
       0 1065.14    12.1 1060.91      16 1058.82    32.7 1048.03    49.3 1034.74
    62.6 1028.78    82.6 1021.54    92.6 1016.12   122.6   992.4   145.9  972.29
   152.5  965.86   162.5  957.98   172.5  948.64   185.7  939.02  190.69936.2522
   211.9  935.08   221.8  936.25   231.6  938.78   254.7  939.16   261.1  940.78
   264.4  942.76   271.1  948.47   287.2  964.47   297.7  973.13   320.2  988.95
   327.6  995.04   344.2 1006.09   384.1  1023.6   417.4 1036.51     427 1042.03
#Mann= 3 ,-1,0
       0      .1       0  190.69    .045       0   221.8      .1       0
Bank Sta=190.69,221.8
XS Rating Curve= 0 ,0
Exp/Cntr(USF)=0,0
Exp/Cntr=0.3,0.1

Type RM Length L Ch R = 1 ,13996   ,197.8,196.2,190.7
XS GIS Cut Line= 2
1642886.25069672475697.4416342381642538.48665898475873.031727952
#Sta/Elev= 30
       0 1049.28    11.1 1045.01    29.2 1033.42    35.5    1030    52.6 1023.63
    62.2 1019.26    73.3 1013.36    80.6 1008.69     110  984.84   124.7  971.35
   138.1  956.98   145.4  946.13   150.5  940.22   154.1  936.43  159.16933.1065
   167.4  932.07  187.79933.1051   205.6  936.52   212.9  936.42   223.6  934.75
   227.6  935.06   240.7  939.04   245.6  941.93   260.7  954.12     281  974.04
   290.1  982.26     331 1007.65   353.8 1020.25   382.3  1029.4   389.6 1032.37
#Mann= 3 ,-1,0
       0      .1       0  159.16    .045       0  187.79      .1       0
Bank Sta=159.16,187.79
XS Rating Curve= 0 ,0
Exp/Cntr(USF)=0,0
Exp/Cntr=0.3,0.1

Type RM Length L Ch R = 1 ,13800   ,124.5,130.7,136.7
XS GIS Cut Line= 6
1642786.39211668475474.4696244151642719.08483659475532.921607256
1642663.34938376475584.6049028341642591.48797892475654.146102339
1642537.59274551   475706.3021661642474.71459043475767.151453748
#Sta/Elev= 30
       0  971.45    19.5     965    42.9  952.24    53.7  948.54    67.3   942.6
    77.9  939.35    92.8  937.71   100.1     936   114.1  934.49   133.8   934.3
   183.4  932.21  201.87928.6432   207.6  927.71   213.9  927.42  221.97928.6427
   233.6  931.55   253.3  932.82     258  934.38   265.2  939.35   278.4  950.25
   297.5  970.66   311.2  981.68   316.1  985.11   344.4  999.99   356.9 1004.66
   369.3 1008.28   386.9 1014.78   393.4 1016.69   415.2 1021.25   427.7 1022.27
#Mann= 3 ,-1,0
       0      .1       0  201.87    .045       0  221.97      .1       0
Bank Sta=201.87,221.97
XS Rating Curve= 0 ,0
Exp/Cntr(USF)=0,0
Exp/Cntr=0.3,0.1

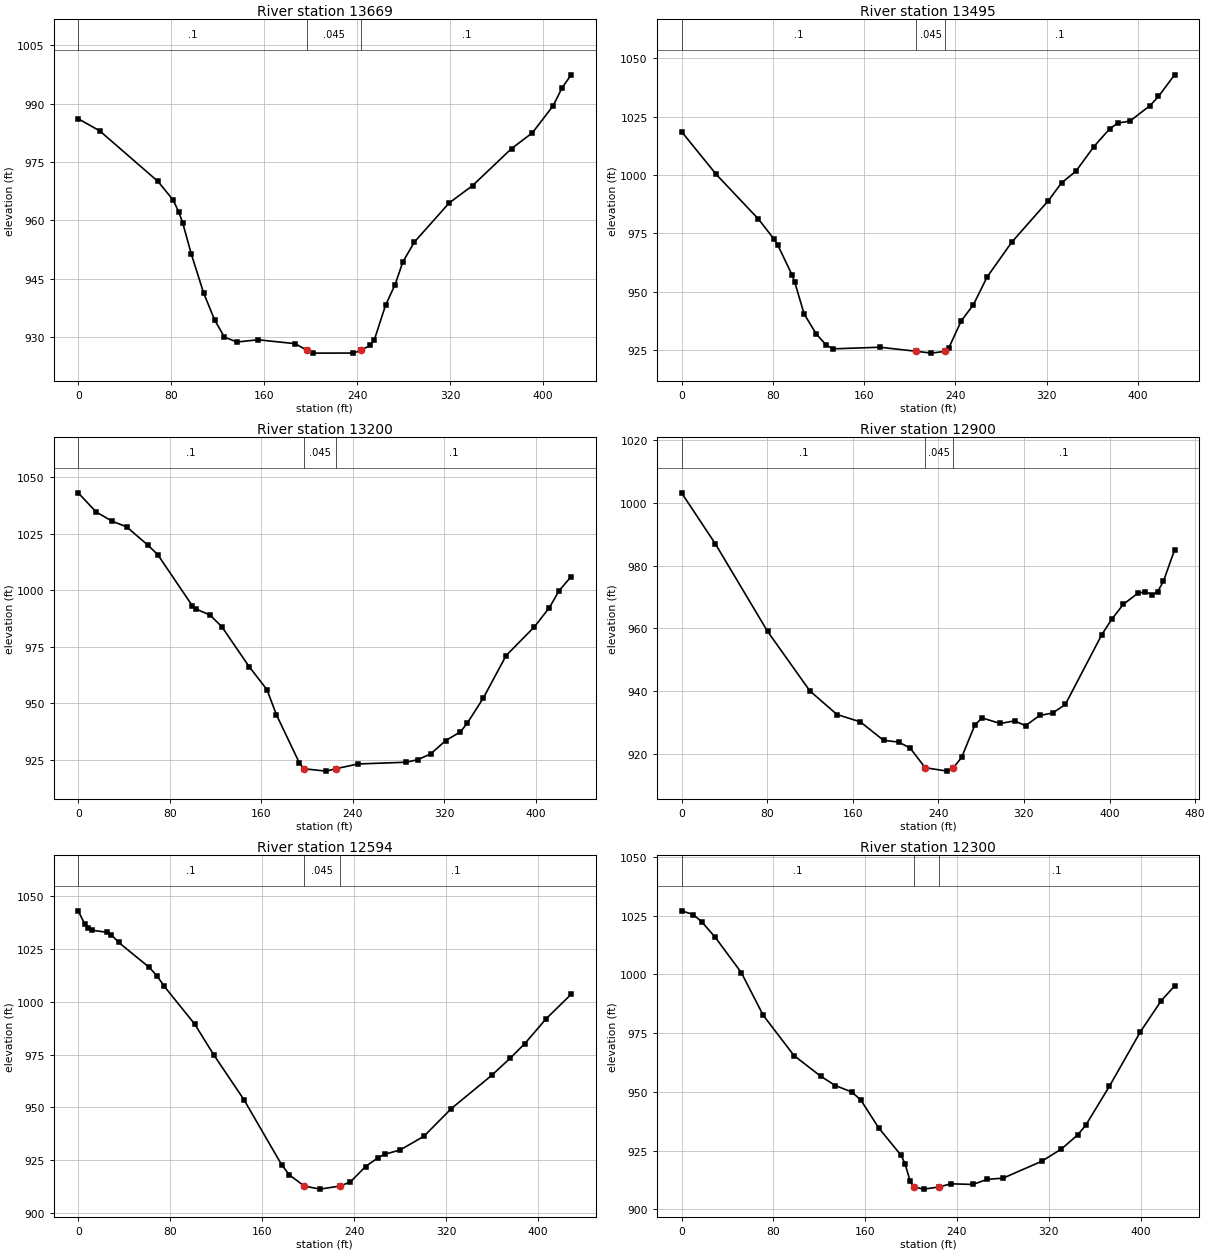
Type RM Length L Ch R = 1 ,13669   ,174.9,174.3,170.2
XS GIS Cut Line= 2
1642755.75377882475424.1496595841642366.99594488475593.590683869
#Sta/Elev= 30
       0  986.11    18.5     983    68.6  970.02    81.4  965.35    86.5  962.24
      90  959.27    97.4  951.27   107.9  941.39   117.3   934.5   125.8  930.04
   136.6   928.8   154.7  929.36   186.7  928.37  196.52926.7023   202.1  925.94
   236.8  925.96   243.6926.7025   251.1  927.94   254.7  929.31   264.4  938.23
   272.6  943.53   279.3  949.37   289.3  954.49   319.2  964.51   339.2  968.93
   372.8  978.45   390.7  982.49   408.6  989.45   416.4  994.12   424.1  997.38
#Mann= 3 ,-1,0
       0      .1       0  196.52    .045       0   243.6      .1       0
Bank Sta=196.52,243.6
XS Rating Curve= 0 ,0
Exp/Cntr(USF)=0,0
Exp/Cntr=0.3,0.1

Type RM Length L Ch R = 1 ,13495   ,299.3,295.1,288.2
XS GIS Cut Line= 6
1642664.27359451475262.9008218351642582.57428284   475301.539196
1642513.99896067475338.7471268331642425.56081735475387.908117756
1642356.74402584475417.728268087 1642276.4577691 475452.51855284
#Sta/Elev= 30
       0 1018.56    30.4 1000.23    67.4  981.09    80.8  972.66    84.5   969.8
    96.8  957.22    99.2  954.12   107.4  940.47   117.9  931.99   126.7  927.13
   132.8   925.5   173.9  926.18   205.6  924.46     219  923.66  231.33  924.46
     234  925.65   245.2  937.51   255.8  944.41   267.8  956.26   289.3  971.13
   321.5  988.98   333.1  996.63   345.6 1001.57   361.4 1012.15   375.1 1019.68
   382.3 1022.21     393 1023.06   410.5 1029.67     418 1033.61   432.1 1042.89
#Mann= 3 ,-1,0
       0      .1       0   205.6    .045       0  231.33      .1       0
Bank Sta=205.6,231.33
XS Rating Curve= 0 ,0
Exp/Cntr(USF)=0,0
Exp/Cntr=0.3,0.1

Type RM Length L Ch R = 1 ,13200   ,284.3,300.2,302.3
XS GIS Cut Line= 6
1642472.60435842474942.2351245881642419.23340218475011.574880928
1642373.18657826 475070.775221841642311.79234409475149.710103333
1642261.96501592 475207.386497171642196.55504176475272.626524165
#Sta/Elev= 30
       0    1043    15.7 1034.54    29.6  1030.5    42.3 1027.99    61.3 1019.75
    69.6 1015.69    99.8  993.13   102.7  991.77   115.2  989.06   125.5  983.96
   149.4  966.32   165.1  956.08   173.4  944.95   193.3  923.87  197.37 921.175
   216.7  920.13  225.13921.1766   244.7  923.29   286.7  924.06   296.8  925.16
   308.3  927.75   321.3   933.6   334.3  937.49   340.2  941.31   354.1  952.27
   374.2  971.15     399  983.88   412.1  992.36   420.5  999.77   431.1 1006.04
#Mann= 3 ,-1,0
       0      .1       0  197.37    .045       0  225.13      .1       0
Bank Sta=197.37,225.13
XS Rating Curve= 0 ,0
Exp/Cntr(USF)=0,0
Exp/Cntr=0.3,0.1

Type RM Length L Ch R = 1 ,12900   ,295,305.3,305.3
XS GIS Cut Line= 6
1642331.78607051474859.8494625841642226.74559817474901.734221339
1642149.56432208474937.797469422  1642052.662613474962.500832096
1641979.93998942474980.8433150951641895.34173343475003.221551165
#Sta/Elev= 30
       0 1003.29    31.6  987.01    80.4  959.07     120  940.06   145.3  932.55
   167.1  930.21   188.8  924.32     203  923.75   213.6  921.85  227.76915.5796
   248.3  914.49  254.07915.5777   261.8  918.87   274.1  929.19   280.9  931.47
   297.8  929.69   311.3  930.53   321.5  928.98   334.7  932.25   346.9  933.04
   358.7  935.75   392.6  957.91     402  962.91   412.9   967.7   426.2  971.18
   433.3  971.74   440.1   970.8     445  971.76   450.4  975.07   460.8  985.04
#Mann= 3 ,-1,0
       0      .1       0  227.76    .045       0  254.07      .1       0
Bank Sta=227.76,254.07
XS Rating Curve= 0 ,0
Exp/Cntr(USF)=0,0
Exp/Cntr=0.3,0.1

Type RM Length L Ch R = 1 ,12594   ,301.4,294.4,284.6
XS GIS Cut Line= 6
1642386.69016017474686.7612260881642299.76841801474675.931523338
1642224.88864651474671.1126353441642124.91673359474656.899081096
1642051.25677593474636.2518126671641966.50760159474610.411313176
#Sta/Elev= 30
       0 1042.98     5.5 1036.91     8.8 1034.94    12.1  1033.8    25.4  1032.8
    28.7 1031.67    35.3    1028    61.7 1016.27    68.3 1012.35    74.9 1007.22
   101.3  989.41   117.8  974.92   144.1  953.66     177  922.77   183.7     918
  196.51 912.809   210.2  911.32  227.98912.8088   236.7  914.77   249.9  922.02
     261  926.28   266.6  927.83   279.9  929.82   300.7  936.36   324.5  949.45
   359.5  965.11   375.9  973.39   388.4  980.19   406.7   991.8   428.7 1003.52
#Mann= 3 ,-1,0
       0      .1       0  196.51    .045       0  227.98      .1       0
Bank Sta=196.51,227.98
XS Rating Curve= 0 ,0
Exp/Cntr(USF)=0,0
Exp/Cntr=0.3,0.1

Type RM Length L Ch R = 1 ,12300   ,294.6,300,304.5
XS GIS Cut Line= 6
1642363.71087542474265.3211240921642288.31174801474309.887964085
1642224.86961767474349.9056005921642141.11256734474404.538693428
1642072.63862292474437.1124471721641986.18243101474465.982796252
#Sta/Elev= 30
       0 1027.06    10.2 1025.49    17.8 1022.25    29.2  1015.9    52.1 1000.74
    71.1  982.64      98  965.44   121.3  956.63     134  952.69   148.4  949.93
   156.2  946.53   171.8  934.65   191.4  922.92   194.7  919.44   199.2     912
  202.45909.5311   210.9  908.59  224.76909.5285   234.5  910.86     254  910.58
   266.3  912.76   280.1  913.25   313.7  920.41     331  925.67   345.1  931.65
   352.1   935.7   372.8  952.35   399.9  975.62     418  988.81   429.6  995.07
#Mann= 3 ,-1,0
       0      .1       0  202.45    .045       0  224.76      .1       0
Bank Sta=202.45,224.76
XS Rating Curve= 0 ,0
Exp/Cntr(USF)=0,0
Exp/Cntr=0.3,0.1

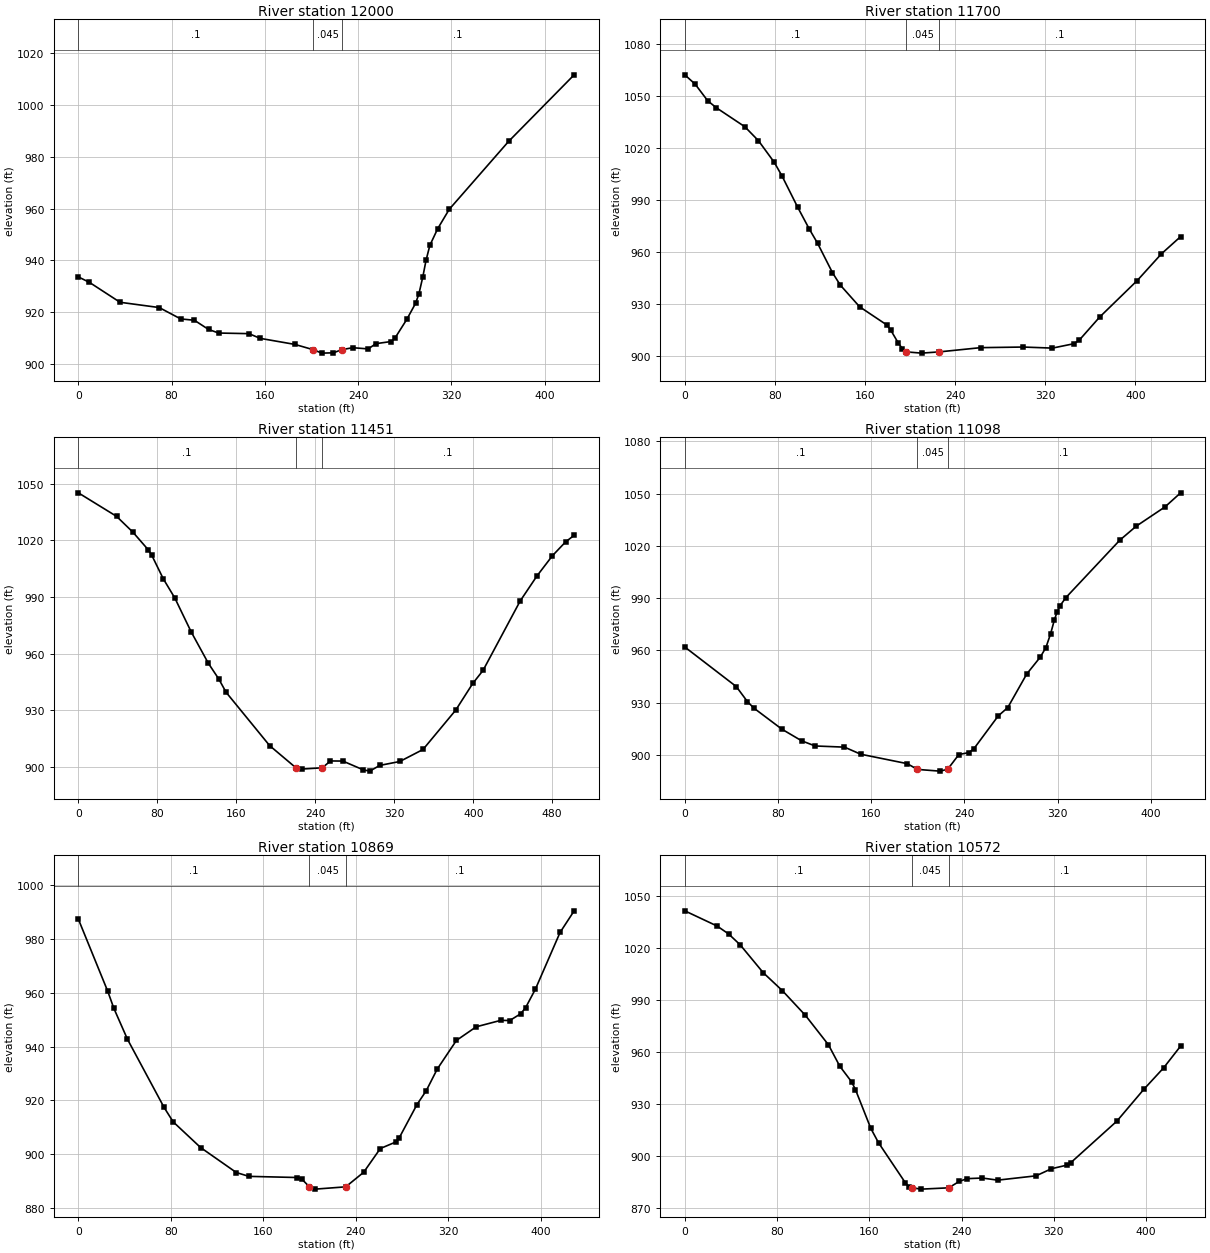
Type RM Length L Ch R = 1 ,12000   ,315.9,300,283
XS GIS Cut Line= 6
 1642317.6325555474056.376988173 1642232.1015586474076.267696425
1642157.92191692474087.4149838391642058.77644593474100.460561424
1641984.49083334474110.8027323341641898.12453626474125.151456922
#Sta/Elev= 30
       0  933.56     9.4  931.48    35.8  923.75    69.4  921.71    87.8  917.32
    99.6  916.79   111.7  913.25   120.4  911.86   146.4  911.62     156   909.8
   185.8  907.46  201.63905.4064   208.9  904.09   218.9  904.21  225.82905.4056
   235.4  906.19   248.7  905.72   255.3  907.75   268.5  908.58   271.8     910
   281.8  917.13   289.3  923.31   292.2  926.99   295.6  933.66   298.3  939.93
   301.6  945.77   308.3  952.18   318.2  959.68   369.1  985.92   425.4 1011.69
#Mann= 3 ,-1,0
       0      .1       0  201.63    .045       0  225.82      .1       0
Bank Sta=201.63,225.82
XS Rating Curve= 0 ,0
Exp/Cntr(USF)=0,0
Exp/Cntr=0.3,0.1

Type RM Length L Ch R = 1 ,11700   ,239.8,248.6,252
XS GIS Cut Line= 6
1642090.48045076473646.9424395861642059.22854476473728.796606585
1642036.78797284473800.3607679161642006.86841325473895.779868424
1641954.99975058473956.5415579231641879.20626701474017.954492837
#Sta/Elev= 30
       0 1061.99     9.2 1056.62    20.3  1047.1    27.9 1043.09    53.3 1032.13
    65.4 1024.08    79.4 1011.66    86.3 1003.79   100.2  985.81   110.5  973.28
   117.8  965.17   131.1  948.15     138  941.06   155.2  928.55   179.3  918.11
   182.7  915.23   189.6  907.62     193  904.56   196.5  902.62   210.2   901.9
  225.85  902.61   262.6  905.05   300.4   905.4   326.3  904.79   345.6  907.35
   350.3  909.49   368.2  922.62   401.6  943.67   423.1  959.04   440.1  968.94
#Mann= 3 ,-1,0
       0      .1       0   196.5    .045       0  225.85      .1       0
Bank Sta=196.5,225.85
XS Rating Curve= 0 ,0
Exp/Cntr(USF)=0,0
Exp/Cntr=0.3,0.1

Type RM Length L Ch R = 1 ,11451   ,347.1,353.1,353.6
XS GIS Cut Line= 5
1641996.78677661473594.5312911541641831.01164376473707.388026216
1641747.28978486473814.7391912781641704.22458229473878.200350447
1641656.03767078473952.802891536
#Sta/Elev= 30
       0 1045.19    38.7 1032.74    55.3 1024.34    70.7 1015.08    74.2 1012.32
      86  999.69    97.8  989.42   114.3  971.54   131.7   954.9   142.2  946.63
   149.7  939.52   193.8  911.28   220.4  899.55   226.3  898.89   247.1  899.55
   255.4  903.18   267.9  903.12   288.7  898.45   295.2  897.79   305.3  900.82
   325.6  902.89   349.1  909.25   382.2  930.07   399.6  944.31   409.9  951.12
   447.5  987.88   464.6 1001.22   480.2 1011.89   493.5 1019.19   502.2 1022.69
#Mann= 3 ,-1,0
       0      .1       0   220.4    .045       0   247.1      .1       0
Bank Sta=220.4,247.1
XS Rating Curve= 0 ,0
Exp/Cntr(USF)=0,0
Exp/Cntr=0.3,0.1

Type RM Length L Ch R = 1 ,11098   ,228.5,229.5,229.9
XS GIS Cut Line= 6
  1641681.994063473418.2526082551641617.65626517473478.043499172
1641561.85355526473528.625419006 1641483.7011525473591.103640512
1641423.58020976473635.9418054221641353.43730542   473688.251084
#Sta/Elev= 30
       0  961.94    44.2  939.22    53.8  930.56    59.4   926.8    83.4  914.73
   100.3  908.07   111.9   905.1   137.1  904.43     151  900.37     191  894.94
  199.71891.6367   218.8  890.65   225.6891.6353   235.3  900.18     244  901.32
   248.2  903.51   269.1  922.37   277.3  927.17   293.6  946.46   305.1  956.05
     310  961.56   314.1   969.6   317.3  977.51   319.6  981.96   322.3  985.74
     327  990.19   373.5 1023.32   387.6 1031.35   412.3 1042.42   425.7  1050.5
#Mann= 3 ,-1,0
       0      .1       0  199.71    .045       0   225.6      .1       0
Bank Sta=199.71,225.6
XS Rating Curve= 0 ,0
Exp/Cntr(USF)=0,0
Exp/Cntr=0.3,0.1

Type RM Length L Ch R = 1 ,10869   ,308.8,297.2,285.2
XS GIS Cut Line= 6
1641550.44096741473265.1241992471641477.67438066473313.805860421
1641415.25455799473355.4580080871641334.83969257473415.183610416
1641275.88377374473464.0660585821641207.16639149473521.190944335
#Sta/Elev= 30
       0  987.45    25.5   960.5    30.7  954.24    42.5   942.7    74.1  917.37
      82  911.97   105.7  902.42   136.6  893.11   147.5  891.68   189.4  891.25
   193.1  890.71  199.81 887.783   204.9  886.93  231.22 887.784   246.7   893.2
   261.1  902.04   274.3  904.44   277.5  906.07   292.8  918.41   300.8  923.56
   310.3   931.6   326.9  942.28     344  947.35   365.3  949.76     373  949.68
   382.4  952.19   386.7  954.46   395.2  961.37   416.5  982.46   428.7  990.52
#Mann= 3 ,-1,0
       0      .1       0  199.81    .045       0  231.22      .1       0
Bank Sta=199.81,231.22
XS Rating Curve= 0 ,0
Exp/Cntr(USF)=0,0
Exp/Cntr=0.3,0.1

Type RM Length L Ch R = 1 ,10572   ,363.7,371.6,373.7
XS GIS Cut Line= 2
1641174.75190419473014.485459504 1641098.5217507473437.672569213
#Sta/Elev= 30
       0 1041.45      28 1032.68      38 1028.11      48 1021.85      68 1005.76
    84.6   995.4   104.6  981.13   124.6  964.12   134.4   951.8   144.6  942.82
     148   938.3   161.3  915.92     168  907.62   191.3  884.49   194.6  882.16
  196.89 881.601   205.2  880.85   228.9881.6009     238   885.3   244.8  886.89
     258  887.26   271.3  886.03   304.6  888.52     318  892.63   331.3  894.68
   334.6  896.02   374.7  920.08     398  938.38   415.2  950.79     430  963.41
#Mann= 3 ,-1,0
       0      .1       0  196.89    .045       0   228.9      .1       0
Bank Sta=196.89,228.9
XS Rating Curve= 0 ,0
Exp/Cntr(USF)=0,0
Exp/Cntr=0.3,0.1