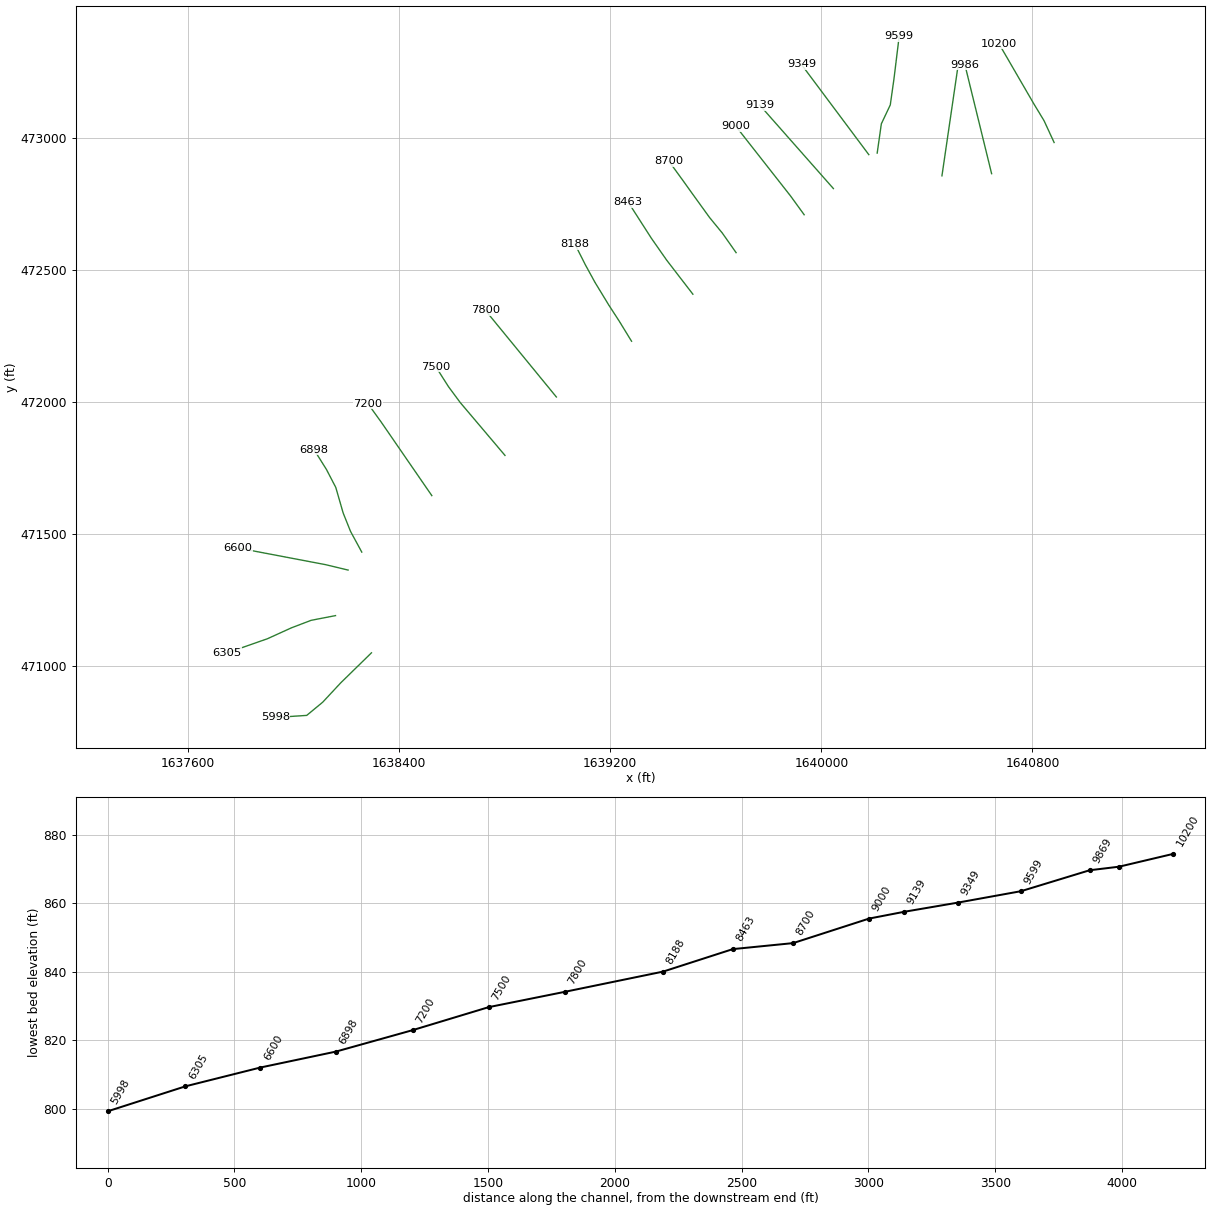
HEC-RAS study UppBwmRn.prj: UppBwmRn

--- UppBwmRn.g01 (geometry) --- (continued)

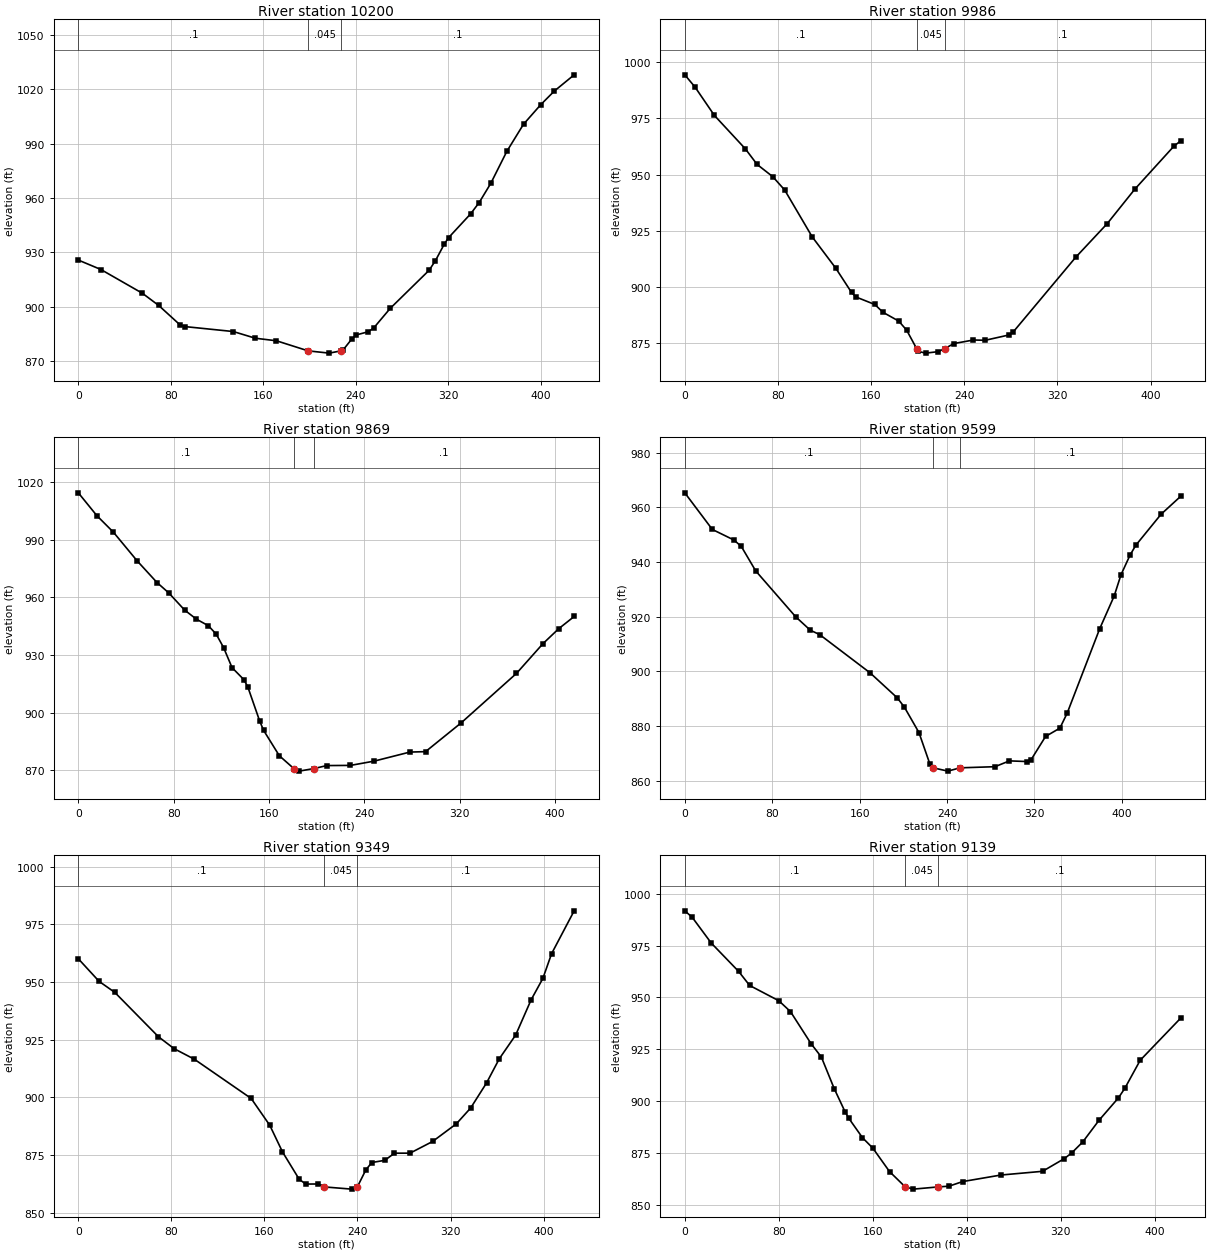
Type RM Length L Ch R = 1 ,10200   ,217.3,214.4,210.4
XS GIS Cut Line= 6
1640881.96285467472981.6691638381640843.91404626473064.208040759
1640804.90231326473128.6075182561640754.71409342473215.101111665
 1640717.0727645473279.9713887571640673.15881035473355.653324008
#Sta/Elev= 30
       0   925.8    19.5  920.59    55.4  907.46    69.5  900.73    88.1  889.91
    91.8  889.09     134  886.33   153.1  882.63   171.3  881.23  198.75875.6536
   216.9  874.41  227.09875.6529   229.1  876.31   236.7  882.42   240.5  884.49
   250.5  886.19   255.3  888.24   269.7  899.15   303.3  920.17   308.8  925.52
   316.4   934.6   320.1  938.16   339.1  951.26   346.5  957.49   356.6  968.16
   370.5  985.85   384.9  1000.8   399.8 1011.61   411.5 1019.11   428.7  1028.1
#Mann= 3 ,-1,0
       0      .1       0  198.75    .045       0  227.09      .1       0
Bank Sta=198.75,227.09
XS Rating Curve= 0 ,0
Exp/Cntr(USF)=0,0
Exp/Cntr=0.3,0.1

Type RM Length L Ch R = 1 ,9986    ,117.9,116.1,111.2
XS GIS Cut Line= 2
1640645.17106703472863.5625641051640543.73616113473277.104872752
#Sta/Elev= 30
       0  994.31     8.8  988.86    25.4  976.28      52  961.42    62.1  954.49
    75.6  949.03    85.8  943.11   109.4  922.32   129.7  908.35   143.2   897.6
   147.1  895.57   163.2  892.26   170.2  888.79   183.7  884.89   190.5  880.87
  199.12  872.62   200.6  871.42   206.8  870.65   217.6   871.3   223.1  872.61
     231   874.9   247.9  876.48     258  876.36   278.3  878.71   281.7  879.85
   335.7  913.24   362.8  928.22   386.4  943.46   420.2   962.7   425.8  964.93
#Mann= 3 ,-1,0
       0      .1       0  199.12    .045       0   223.1      .1       0
Bank Sta=199.12,223.1
XS Rating Curve= 0 ,0
Exp/Cntr(USF)=0,0
Exp/Cntr=0.3,0.1

Type RM Length L Ch R = 1 ,9869    ,265.1,270.4,268.8
XS GIS Cut Line= 2
1640456.98789607472855.3394331151640517.24770483473267.080666512
#Sta/Elev= 30
       0 1014.38    15.6 1002.47    29.5  993.86    49.4  978.96      66  967.73
    75.9  962.31    89.2  953.39    99.1  948.66   109.1  945.26   115.7  940.87
   121.9  933.88     129  923.45   138.9  917.21   142.2  913.46   152.2  895.64
   155.5   890.8   168.7   877.6  180.81  870.97   185.3  869.61   197.9  870.97
   208.5   872.5   228.4  872.59   248.3  874.82   278.2  879.52   291.4  879.75
   321.3  894.73   367.7  920.46   389.9  935.91   403.2  943.73   416.1  950.05
#Mann= 3 ,-1,0
       0      .1       0  180.81    .045       0   197.9      .1       0
Bank Sta=180.81,197.9
XS Rating Curve= 0 ,0
Exp/Cntr(USF)=0,0
Exp/Cntr=0.3,0.1

Type RM Length L Ch R = 1 ,9599    ,237.1,250.5,258.1
XS GIS Cut Line= 6
1640211.68762042472941.6265930091640227.40806143473052.475780755
1640261.29382043 473124.178393261640275.30527534473223.209691256
1640284.40466659473297.6557365951640295.02144326473384.509237424
#Sta/Elev= 30
       0  965.31    25.2  951.91      45  948.04    51.7  945.71    64.9  936.75
   101.4     920   114.9  915.04   123.4  913.46   169.5  899.48   194.5  890.29
     201  886.89   214.3  877.62   224.2  866.22  227.32864.7073   240.8   863.5
  251.85864.7054   283.9  865.12   297.1  867.25   313.6     867   316.9  867.65
   330.2  876.19   343.3  879.23     350  884.74   379.7  915.56     393  927.58
   399.2  935.31   407.5  942.52   412.8  946.14   435.9  957.47   453.8  964.02
#Mann= 3 ,-1,0
       0      .1       0  227.32    .045       0  251.85      .1       0
Bank Sta=227.32,251.85
XS Rating Curve= 0 ,0
Exp/Cntr(USF)=0,0
Exp/Cntr=0.3,0.1

Type RM Length L Ch R = 1 ,9349    ,205.9,209.4,208.3
XS GIS Cut Line= 2
1640179.86423231 472935.791797481639924.74273089 473277.32536426
#Sta/Elev= 30
       0     960    17.9  950.19    31.4  945.41    68.9  926.19    82.3  921.05
    99.8  916.44   148.6  899.45   164.6  887.82   175.5   876.3   189.9  864.41
   195.5  862.33   206.3  862.37  211.52861.0989   234.9  860.14  239.91861.1259
   247.2  868.49   252.3  871.67   263.5  872.63   271.8  875.72   285.2  875.74
   304.6   880.8     325  888.45   337.3   895.3     351   906.2   361.9  916.63
     376  926.93   389.3  942.22   399.4  951.49   406.9  962.22   426.3  980.79
#Mann= 3 ,-1,0
       0      .1       0  211.52    .045       0  239.91      .1       0
Bank Sta=211.52,239.91
XS Rating Curve= 0 ,0
Exp/Cntr(USF)=0,0
Exp/Cntr=0.3,0.1

Type RM Length L Ch R = 1 ,9139    ,137.4,139.2,133.8
XS GIS Cut Line= 2
1640045.75157111472807.2441975581639766.55514021473123.554353408
#Sta/Elev= 30
       0  991.82     6.3   988.7    22.5  976.27    45.8  962.58    55.2  955.79
      80  948.42    89.9  943.19   107.4  927.73   116.2  921.25   127.1  906.05
   136.4  894.78   139.5  891.72   151.2   882.3     160  877.28   174.2  865.97
   187.6  858.55   194.5  857.49   215.8858.5692   224.8  858.91   236.4  861.13
   268.9  864.29   304.4  866.09     323  872.24   329.3  875.01   338.6  880.24
   352.5  890.75   368.9  901.48   374.4  906.13   387.5  919.69   421.9  939.99
#Mann= 3 ,-1,0
       0      .1       0   187.6    .045       0   215.8      .1       0
Bank Sta=187.6,215.8
XS Rating Curve= 0 ,0
Exp/Cntr(USF)=0,0
Exp/Cntr=0.3,0.1

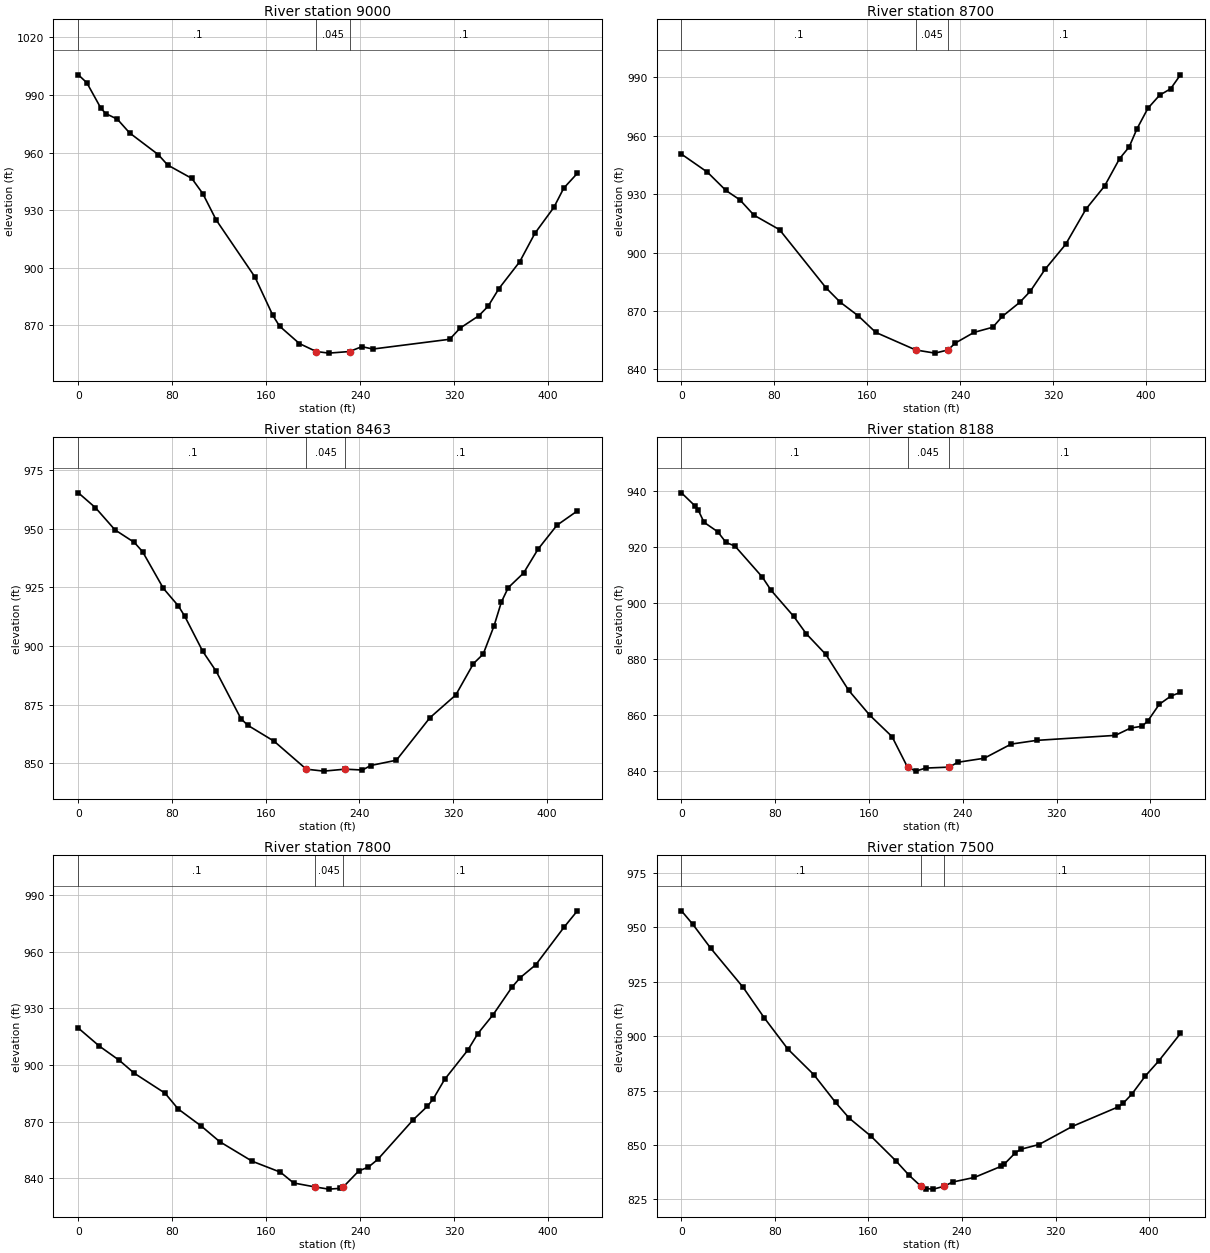
Type RM Length L Ch R = 1 ,9000    ,298.4,299.8,297
XS GIS Cut Line= 6
1639934.99394809472708.1119681751639883.58755484 472778.99666892
1639837.28416976472837.9965509181639775.54610425472916.663060263
1639729.24271917472975.6632703391639675.22215793473044.496466011
#Sta/Elev= 30
       0 1000.53     7.2  996.39    19.3  983.01    23.4  980.32    33.2  977.42
    43.6  970.28      68  958.98    76.1  953.52    96.6  946.57     106  938.63
   117.4   924.9   150.4  895.19   165.7  875.13   171.4  869.56   188.3  860.48
  202.66856.3386   213.4   855.5     231856.3384   241.5  858.87   250.9  857.63
   316.3  862.72   325.2  868.53   341.1  874.96     349  879.89   358.3  889.16
     376  903.14   388.9  917.92   405.1  931.48   413.5  941.49   425.1  949.22
#Mann= 3 ,-1,0
       0      .1       0  202.66    .045       0     231      .1       0
Bank Sta=202.66,231
XS Rating Curve= 0 ,0
Exp/Cntr(USF)=0,0
Exp/Cntr=0.3,0.1

Type RM Length L Ch R = 1 ,8700    ,232.6,237.6,230.6
XS GIS Cut Line= 6
1639677.14669476472564.4636334181639625.16549951 472638.40147768
1639576.56060985472697.6208474191639518.00396842472778.731905669
1639474.33837333472839.6678074151639422.94411917472910.466878429
#Sta/Elev= 30
       0  950.61    22.3  941.35    38.3  931.92    50.3  927.11    62.4  919.23
    84.4  911.78   124.4   881.9   136.6  874.54   152.2  867.48   167.2     859
  201.65849.9509   218.2  848.33  229.38849.9528   235.6  853.47   251.8  858.99
     268  861.64   276.1  867.16   291.2  874.44   300.3  880.17   312.9  891.36
   330.6  904.17   348.2  922.38   364.2  934.22   377.1  948.29   385.3  954.25
   392.1  963.66   401.5  974.18   411.6  980.92     421  984.17   429.5  991.36
#Mann= 3 ,-1,0
       0      .1       0  201.65    .045       0  229.38      .1       0
Bank Sta=201.65,229.38
XS Rating Curve= 0 ,0
Exp/Cntr(USF)=0,0
Exp/Cntr=0.3,0.1

Type RM Length L Ch R = 1 ,8463    ,276.2,275,273.7
XS GIS Cut Line= 6
1639513.43926031 472407.065780451639459.71955148 472476.73690096
1639413.79214989 472536.531400791639356.41529614472618.625724797
1639315.90487847472681.7338662941639268.64414622472755.357406711
#Sta/Elev= 30
       0   965.3    14.6  958.95    31.2  949.52    47.8  944.13    54.8  940.21
    72.6  924.52    85.4  917.03    90.8  912.67   106.2  897.67   117.7  889.14
   138.8  868.94   144.6  866.15   167.1  859.33   194.6 847.414   209.5  846.58
   227.7  847.42   242.5  847.05   249.6  848.98   271.5  851.24   300.1  869.35
   322.2  879.07   337.3  892.46   345.6   896.5   354.8  908.46   361.2  918.82
     367  924.85   380.1   931.1   392.4  941.24   408.5  951.45     426  957.59
#Mann= 3 ,-1,0
       0      .1       0   194.6    .045       0   227.7      .1       0
Bank Sta=194.6,227.7
XS Rating Curve= 0 ,0
Exp/Cntr(USF)=0,0
Exp/Cntr=0.3,0.1

Type RM Length L Ch R = 1 ,8188    ,384.7,387.6,388.9
XS GIS Cut Line= 6
1639281.07149943472228.7888339351639235.39016036472303.416637439
1639194.60448077472366.3574564351639142.57965044 472451.80479211
1639106.42453903472517.7462612731639066.69988094472596.269398186
#Sta/Elev= 30
       0  939.19    11.8  934.43    14.2  933.12    19.3  928.67    30.9  925.33
      38  921.52    45.7   920.2      69  909.16    76.4  904.48    95.8  895.14
   106.4     889   123.2  881.58   142.6  868.83   160.7  859.91   179.6  852.33
  192.84841.4353   199.9  840.01   208.3   841.1  228.44 841.438   235.7  843.16
   258.3   844.6   281.2  849.64     303  850.97   370.1  852.75   383.2  855.37
     393  856.01   397.9  857.93   407.6  863.81   417.4  866.73   425.7  868.08
#Mann= 3 ,-1,0
       0      .1       0  192.84    .045       0  228.44      .1       0
Bank Sta=192.84,228.44
XS Rating Curve= 0 ,0
Exp/Cntr(USF)=0,0
Exp/Cntr=0.3,0.1

Type RM Length L Ch R = 1 ,7800    ,299,300,300.1
XS GIS Cut Line= 6
1638996.25041875472017.6517349181638940.79744567472085.336310834
1638893.26637276472143.3516147581638829.89215568472220.706446916
1638782.36141084472278.7217508411638726.90909392472346.406982929
#Sta/Elev= 30
       0  919.58    17.9  910.01    34.9  902.46    47.6  895.63    73.8  885.04
      85  876.65   104.8  867.51   120.4  859.29     148  848.92   172.1  843.09
   183.3  837.37  201.25835.2938   213.2   834.1   222.6  834.49  225.69835.2957
   238.9  843.81   246.9  845.75     255  849.88   285.1  870.87   297.2  878.06
   302.1  881.86   311.9  892.31   331.8  907.99   340.2  916.64   353.3  926.76
   369.4  941.41   376.4  946.41   389.6  953.23   413.7   973.2     425  981.85
#Mann= 3 ,-1,0
       0      .1       0  201.25    .045       0  225.69      .1       0
Bank Sta=201.25,225.69
XS Rating Curve= 0 ,0
Exp/Cntr(USF)=0,0
Exp/Cntr=0.3,0.1

Type RM Length L Ch R = 1 ,7500    ,299.3,300,297.6
XS GIS Cut Line= 6
1638801.64254026471796.269959837 1638745.1006586471863.047713429
1638696.63651668471920.2857879251638632.01722334471996.603220582
1638587.32669592 472057.036826761638539.41570251472132.367384762
#Sta/Elev= 30
       0  957.66     9.8   951.4      25  940.47    52.7   922.5    70.7  908.53
      91  894.08   113.2  882.31   131.8  869.55   143.5  862.28   162.1     854
   183.6  842.56   194.7  836.02  204.84830.9688   209.4   829.9   215.6  829.63
  224.79830.9689   231.9  832.88   250.6  835.01   273.3  840.09   276.3   841.2
   285.6  846.32   290.3  847.96   305.9  850.15   334.5  858.51   373.5  867.43
   377.7  869.04   385.2  873.26   396.8  881.65   408.3  888.58   426.9  901.25
#Mann= 3 ,-1,0
       0      .1       0  204.84    .045       0  224.79      .1       0
Bank Sta=204.84,224.79
XS Rating Curve= 0 ,0
Exp/Cntr(USF)=0,0
Exp/Cntr=0.3,0.1

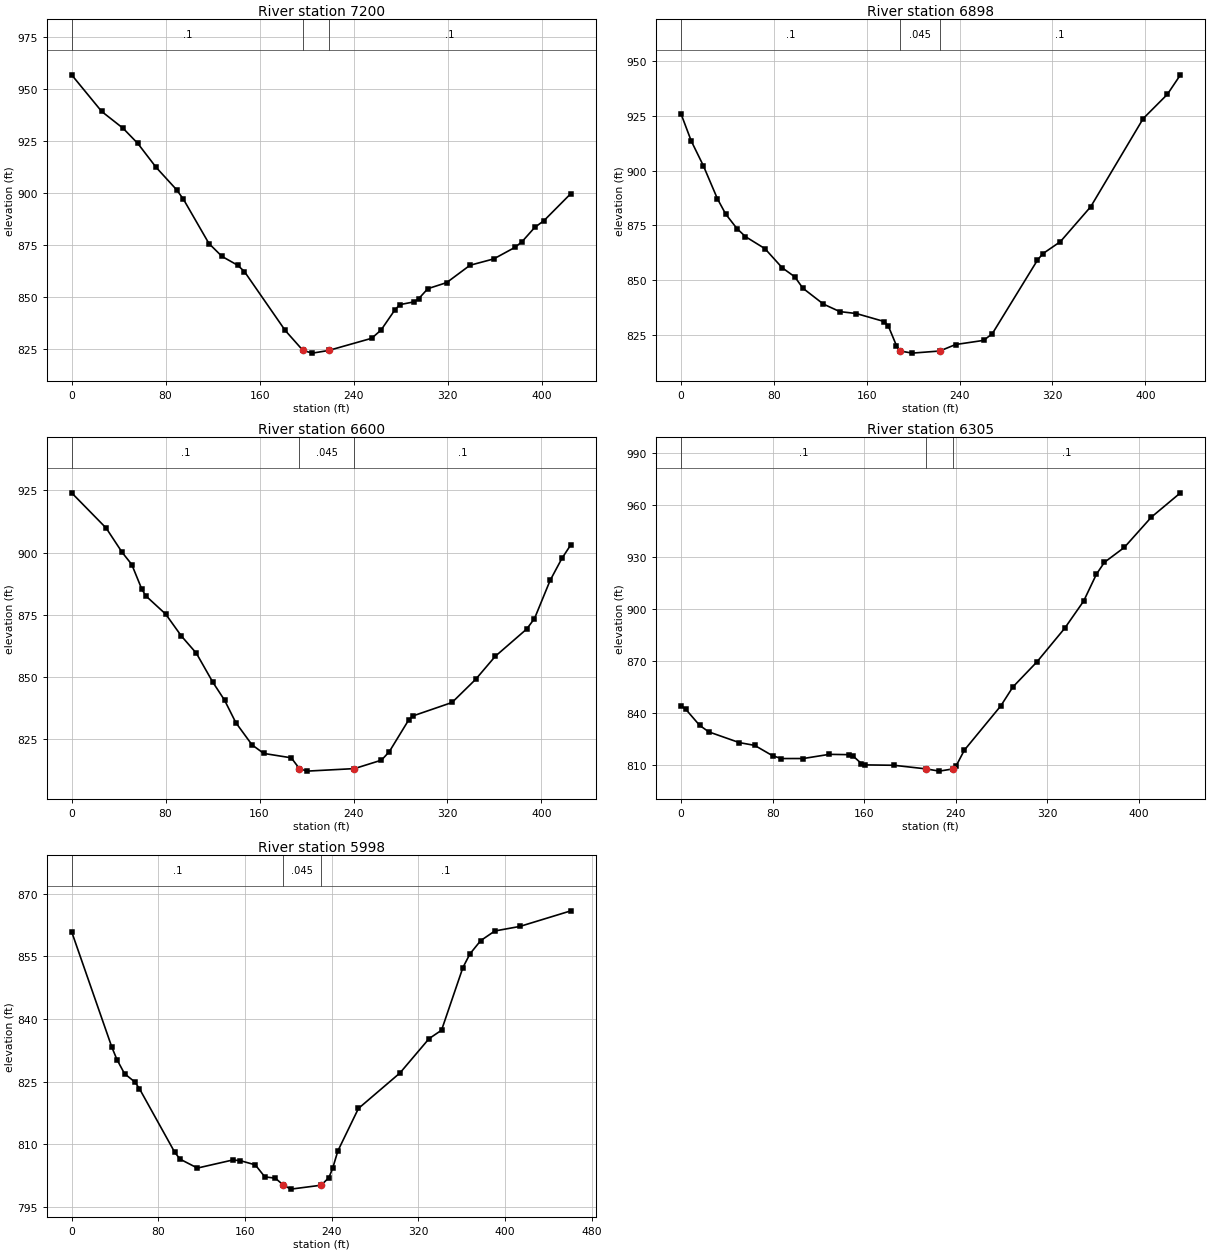
Type RM Length L Ch R = 1 ,7200    ,311.4,302.3,299.2
XS GIS Cut Line= 6
1638524.41868526471643.9556319271638474.79739343471716.025041595
1638432.26499817471777.7988681791638375.55546592471860.164189011
1638333.02307068471921.9376875011638281.85683443471992.943451002
#Sta/Elev= 30
       0   956.7    25.6  939.08    43.8     931    56.3  923.73    71.9  912.23
    89.3  901.48    95.1  896.95   116.9  875.59     128   869.4   141.4  865.14
   147.1  862.11   181.8  833.81  196.93824.1965     205  822.91   218.8824.1967
   255.4  830.04   263.4  834.01     275  843.56   279.3  846.21   291.8  847.59
   295.3     849   303.2  853.89   319.2   856.8   339.1  865.15   359.3   868.2
   377.3  873.73   383.3  876.42   394.2  883.34   402.1  886.61     425  899.64
#Mann= 3 ,-1,0
       0      .1       0  196.93    .045       0   218.8      .1       0
Bank Sta=196.93,218.8
XS Rating Curve= 0 ,0
Exp/Cntr(USF)=0,0
Exp/Cntr=0.3,0.1

Type RM Length L Ch R = 1 ,6898    ,270.5,297.7,315.5
XS GIS Cut Line= 6
1638259.05897975471430.0029758361638216.50788376471508.345010757
1638188.36030225471578.6818123461638160.65038392471674.873549089
1638125.45819709471742.5797785071638078.27489251 471818.06945692
#Sta/Elev= 30
       0  925.83     8.7  913.59    19.1  902.33    31.3  887.13    38.4  880.19
    48.1  873.57    55.4   869.9    72.2   864.4    87.1  855.65    97.9  851.53
   104.9  846.32   122.6  839.06   136.7  835.63   150.9  834.75   175.2  831.06
   178.6  828.95   185.5  820.13  188.73 817.622   199.1  816.65  222.88 817.621
   236.5  820.58   260.6  822.47   268.1  825.49     307   859.1   311.6  862.06
   326.8  867.59     353  883.59   398.2  923.86     419  934.92   430.3  943.85
#Mann= 3 ,-1,0
       0      .1       0  188.73    .045       0  222.88      .1       0
Bank Sta=188.73,222.88
XS Rating Curve= 0 ,0
Exp/Cntr(USF)=0,0
Exp/Cntr=0.3,0.1

Type RM Length L Ch R = 1 ,6600    ,290,295.5,303.3
XS GIS Cut Line= 6
1638207.16177385471361.9371670931638121.98543501471382.403661594
 1638048.3048081 471396.409211011637950.06386285471415.083058178
1637876.38290784471429.0886075941637790.42212176471445.428141832
#Sta/Elev= 30
       0  924.04    29.4  909.85      43  900.08    51.2  895.18    59.8   885.2
    63.2  882.54    80.1   875.2    93.5  866.36   106.2  859.46   120.2  847.81
   130.2  840.57   139.8  831.52   153.6  822.57   163.6  819.12     187  817.36
  193.91813.0175   200.4     812  240.82813.0182   263.8  816.42   270.5  819.85
   287.2  832.77   290.5  834.21   323.9  839.64     344  848.95   360.7  858.23
   387.4  869.18   394.1  873.42   407.4  888.77   417.4  897.61   425.1  903.18
#Mann= 3 ,-1,0
       0      .1       0  193.91    .045       0  240.82      .1       0
Bank Sta=193.91,240.82
XS Rating Curve= 0 ,0
Exp/Cntr(USF)=0,0
Exp/Cntr=0.3,0.1

Type RM Length L Ch R = 1 ,6305    ,299.8,306.9,309.6
XS GIS Cut Line= 6
1638159.53326017 471189.382394091638067.27097751471171.544175178
 1637993.1100366471143.3086673321637901.70372334471101.760194004
1637830.91416676471076.983996838 1637748.3267335471048.078542843
#Sta/Elev= 30
       0  844.15     4.1  842.08    16.1  832.91    24.1  829.13    50.8  822.94
    64.2  821.35    79.9  815.37    87.6  813.76   106.6  813.77   129.4  816.18
     147  815.99   150.5  815.03   157.5  810.84     161   810.1   185.9  809.88
  214.18807.7833   225.5  806.51  237.48807.7849     240  809.22   247.4   818.6
   279.2  844.07   289.8  854.99   310.7  869.37     335  888.76   351.6  904.45
   362.8  919.99   369.8  926.84   387.1  935.37   410.8  952.86   436.2  966.86
#Mann= 3 ,-1,0
       0      .1       0  214.18    .045       0  237.48      .1       0
Bank Sta=214.18,237.48
XS Rating Curve= 0 ,0
Exp/Cntr(USF)=0,0
Exp/Cntr=0.3,0.1

Type RM Length L Ch R = 1 ,5998    ,322.2,300.8,275.2
XS GIS Cut Line= 6
1638295.71868335471048.325589582 1638233.1174306470987.191525504
1638179.45940143 470934.791039751638111.22889484470861.530687585
1638050.51084043470811.3549349161637931.37558001470803.474701345
#Sta/Elev= 30
       0  860.93    37.2  833.18    41.9  830.23    48.8   826.9    58.4  824.88
    62.6  823.28    95.2  808.02   100.1  806.39   116.1  804.26   148.6  806.19
   155.6  806.04   169.5  805.03   178.3  802.15     188  801.84  195.52800.1513
   202.4  799.21  230.31800.1512   237.4  801.96   240.9  804.19   245.7  808.36
   264.7  818.55     303  827.05   329.9  835.29   341.4  837.31   361.1  852.32
   367.6   855.6   377.5  858.78   390.6   861.1   413.7  862.19   460.8  865.93
#Mann= 3 ,-1,0
       0      .1       0  195.52    .045       0  230.31      .1       0
Bank Sta=195.52,230.31
XS Rating Curve= 0 ,0
Exp/Cntr(USF)=0,0
Exp/Cntr=0.3,0.1