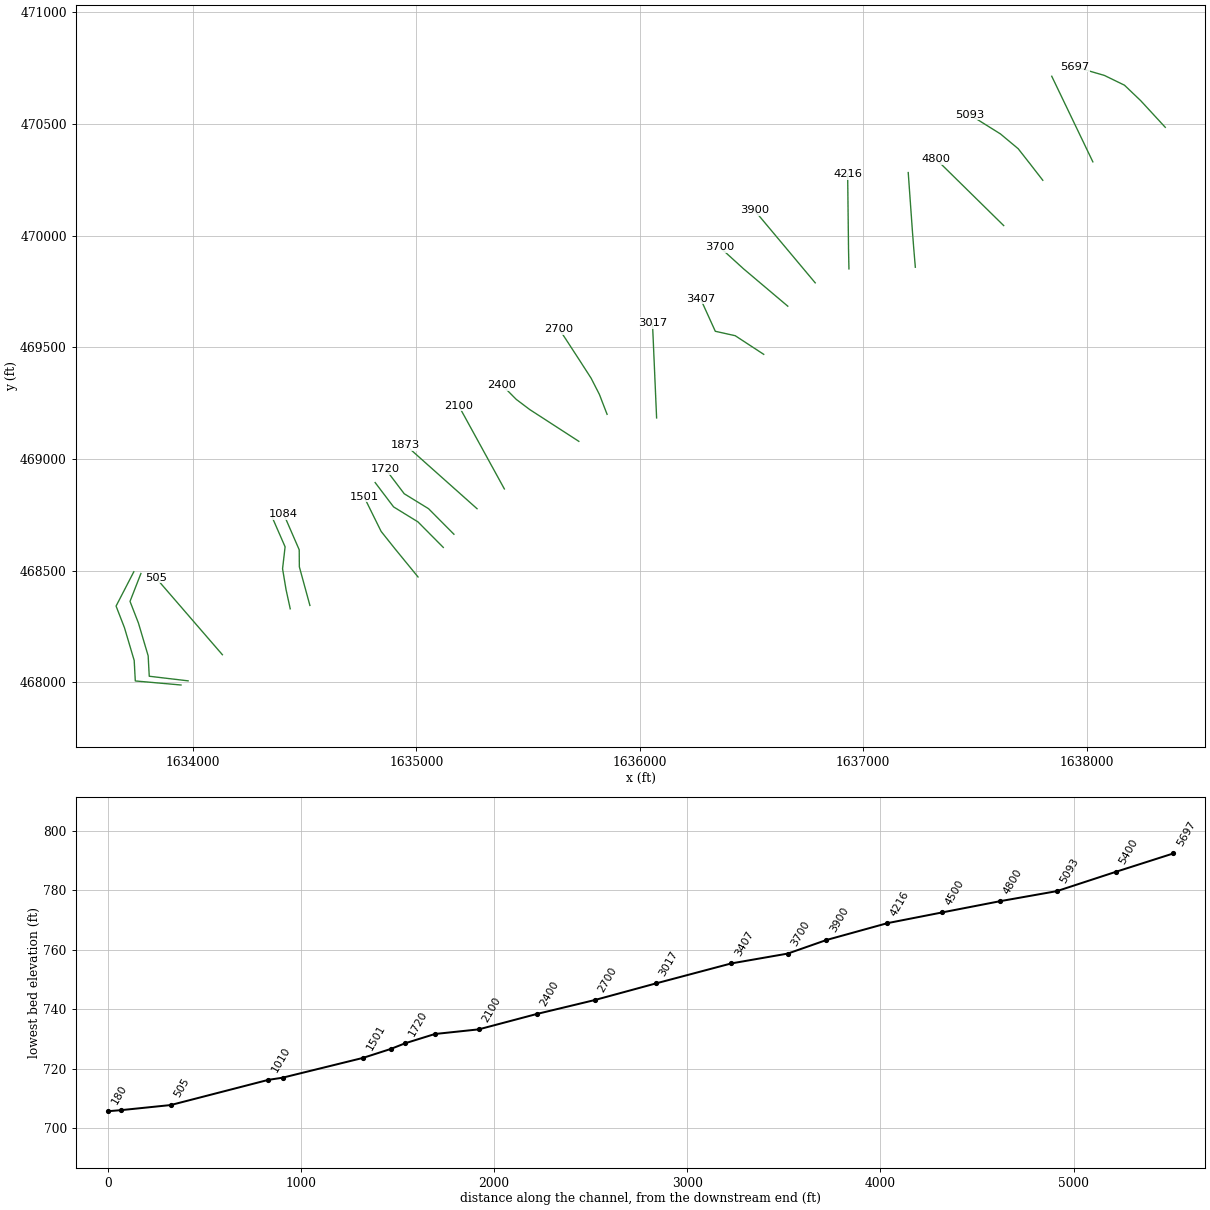
HEC-RAS study UppBwmRn.prj: UppBwmRn

--- UppBwmRn.g01 (geometry) --- (continued)

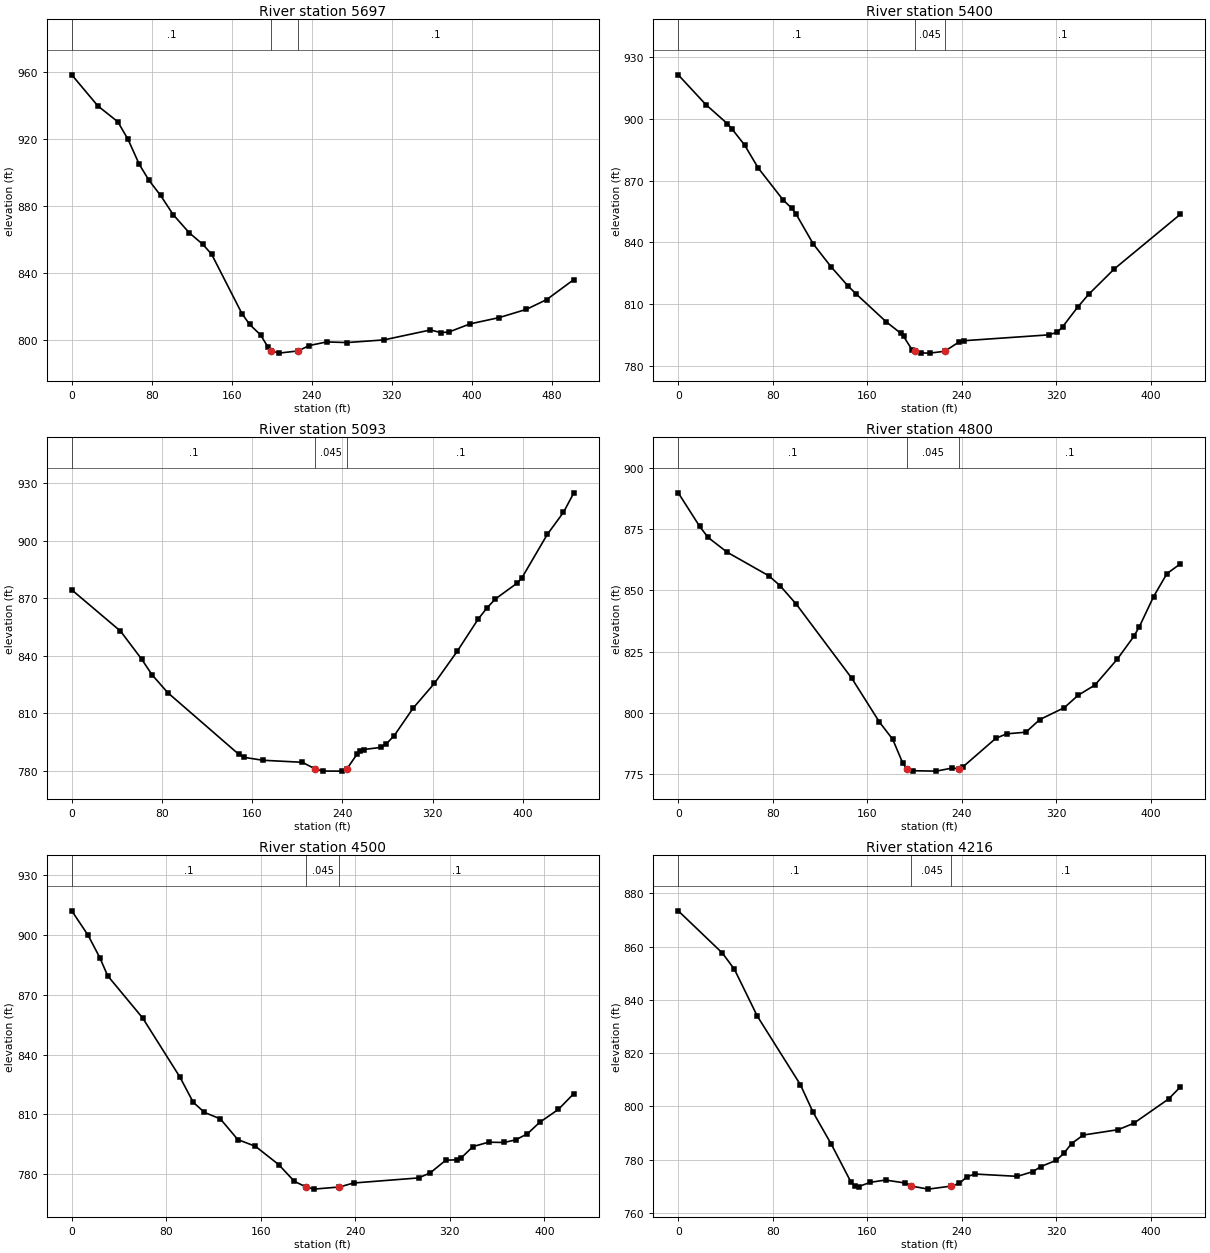
Type RM Length L Ch R = 1 ,5697    ,301.2,296.8,291.5
XS GIS Cut Line= 6
1638352.25170676470485.2450228331638292.93719284 470549.57265009
1638242.09575909470604.7103350911638169.58081226470673.868661344
1638079.68696317470717.5237577561637945.96347734470756.559440836
#Sta/Elev= 30
       0  958.27    26.1  939.72      46   930.3    56.3  919.73    67.5  904.85
    77.2  895.37    88.8  886.36   101.4  874.91   117.4  864.11   130.8  857.32
   139.7  851.43   170.1  815.94   177.8  809.45   188.7  803.25     196  796.08
  199.62793.6826   207.2  792.36  226.23793.6816   237.4  796.88   254.9  799.04
   275.2  798.66     312  800.24   358.5  806.16   368.9  804.63   376.9  804.92
     398  809.77   427.2  813.53   454.5  818.47   474.8  824.29   501.9  836.22
#Mann= 3 ,-1,0
       0      .1       0  199.62    .045       0  226.23      .1       0
Bank Sta=199.62,226.23
XS Rating Curve= 0 ,0
Exp/Cntr(USF)=0,0
Exp/Cntr=0.3,0.1

Type RM Length L Ch R = 1 ,5400    ,296.6,306.9,309.4
XS GIS Cut Line= 6
 1638028.0646911470330.7062899171637990.18386135470409.581460252
1637957.71476617470477.1889365911637914.42252992470567.331800923
1637881.95310667470634.9392772621637844.07227692470713.814447582
#Sta/Elev= 30
       0  921.32    23.3  906.91    41.5  897.65    45.2  895.26    56.1   887.3
    67.7  876.08    88.8  860.56    96.1  856.54    99.8  853.67   114.3   839.2
   129.2  828.23   143.4  818.99   150.7  814.87   176.2  801.32   188.2  795.92
   190.8  794.31     198  787.73  200.13787.0995   205.3  786.29   212.8   786.2
  225.58787.0988   237.4  791.51   241.7  792.22   313.6  795.07     321  796.37
   325.4  799.01   338.2  808.59   347.3  814.68   369.1  827.07     425  853.59
#Mann= 3 ,-1,0
       0      .1       0  200.13    .045       0  225.58      .1       0
Bank Sta=200.13,225.58
XS Rating Curve= 0 ,0
Exp/Cntr(USF)=0,0
Exp/Cntr=0.3,0.1

Type RM Length L Ch R = 1 ,5093    ,294.4,293.1,290.8
XS GIS Cut Line= 6
1637804.09171385470248.0909695921637745.52785459 470323.55669792
1637693.87802351470389.4056475911637614.35390434470455.679793254
1637550.77857217470495.4113410861637476.61008534470541.763938665
#Sta/Elev= 30
       0   874.4    43.2  852.86    61.9  838.25    71.2  830.02      85  820.74
     148  788.51     153  786.87   169.4  785.36   204.4   784.3  215.83780.8416
     223  779.72   239.3  779.68  243.93780.8408     253  788.58   255.6  789.95
   258.7  790.96   274.3   792.1   278.9   793.9     286  798.29   302.6  812.53
   321.6  825.58   341.8  842.32   360.3  859.07     368  864.87   375.7  869.69
   395.1     878     399  880.55   421.7  903.43     436  914.92   445.2  925.12
#Mann= 3 ,-1,0
       0      .1       0  215.83    .045       0  243.93      .1       0
Bank Sta=215.83,243.93
XS Rating Curve= 0 ,0
Exp/Cntr(USF)=0,0
Exp/Cntr=0.3,0.1

Type RM Length L Ch R = 1 ,4800    ,311.5,300,285.6
XS GIS Cut Line= 6
1637628.90079126470045.3617162561637566.49343576470106.693614587
1637513.00174484470159.2637194251637441.67905284 470229.35741125
   1637388.18769470281.927844167 1637325.7803345 470343.25941442
#Sta/Elev= 30
       0  889.75    18.2  876.03    25.2  871.59    41.4  865.55    76.7  855.92
    86.1  851.96   100.1  844.26   146.9  814.16   170.3  796.31   181.6  789.24
   189.9  779.74  193.26777.3265   198.4  776.47   218.4  776.31   231.7  777.55
  237.44777.3253     241  778.04   268.8  789.68     278  791.51   294.3  792.18
     306  797.31   326.8  802.18   338.4  807.19   352.8  811.43   371.6  821.92
   385.6  831.19   390.3  835.14   402.4  847.47   413.7  856.84     425  860.78
#Mann= 3 ,-1,0
       0      .1       0  193.26    .045       0  237.44      .1       0
Bank Sta=193.26,237.44
XS Rating Curve= 0 ,0
Exp/Cntr(USF)=0,0
Exp/Cntr=0.3,0.1

Type RM Length L Ch R = 1 ,4500    ,284.9,284.1,283.2
XS GIS Cut Line= 6
1637233.37960067469858.8679947561637226.07318485469946.068935841
1637220.31433809470020.8486419171637213.18935233470120.594505429
1637207.84618717470195.4040670841637201.61194767470282.681779668
#Sta/Elev= 30
       0  912.07    13.9  899.74    23.8   888.5    30.4   879.5      60  858.35
    91.6  828.66   102.8  816.08   112.3  811.01   125.8  807.73   140.5   797.4
   155.5  793.98   175.2  784.81   188.3  776.49  198.29773.6022   204.9  772.53
  226.53773.6007   238.6   775.6   293.6  778.15   303.5  780.71   316.6  787.04
   326.5  787.23   329.8  788.28   339.6  793.86   352.8  796.06     366  795.92
   375.8  797.24   385.7  800.28     396  805.98     412  812.55     425  820.45
#Mann= 3 ,-1,0
       0      .1       0  198.29    .045       0  226.53      .1       0
Bank Sta=198.29,226.53
XS Rating Curve= 0 ,0
Exp/Cntr(USF)=0,0
Exp/Cntr=0.3,0.1

Type RM Length L Ch R = 1 ,4216    ,305.1,315.9,326.2
XS GIS Cut Line= 6
1636936.20954013469851.4231277561636934.36079054469938.907532841
1636933.47627787470013.9024615881636932.29714638470113.895371839
 1636931.4126337470188.8899725081636930.38081163   470276.383892
#Sta/Elev= 30
       0  873.46    37.4  857.58    47.6  851.45      67  833.85   103.4  808.15
   114.2  797.73   129.6  785.77     146  771.75   149.3  770.12   152.6  769.84
   162.5  771.48   175.5  772.33   191.9  771.23  197.37770.0642   211.6  768.92
   231.3  770.07   237.9  771.06   244.4  773.57     251  774.59   287.1  773.72
   300.3  775.51   306.8  777.37   320.1  779.76   326.5  782.42     333  786.05
   342.9  789.24   372.4  791.25   385.5  793.63   415.1  802.79     425  807.29
#Mann= 3 ,-1,0
       0      .1       0  197.37    .045       0   231.3      .1       0
Bank Sta=197.37,231.3
XS Rating Curve= 0 ,0
Exp/Cntr(USF)=0,0
Exp/Cntr=0.3,0.1

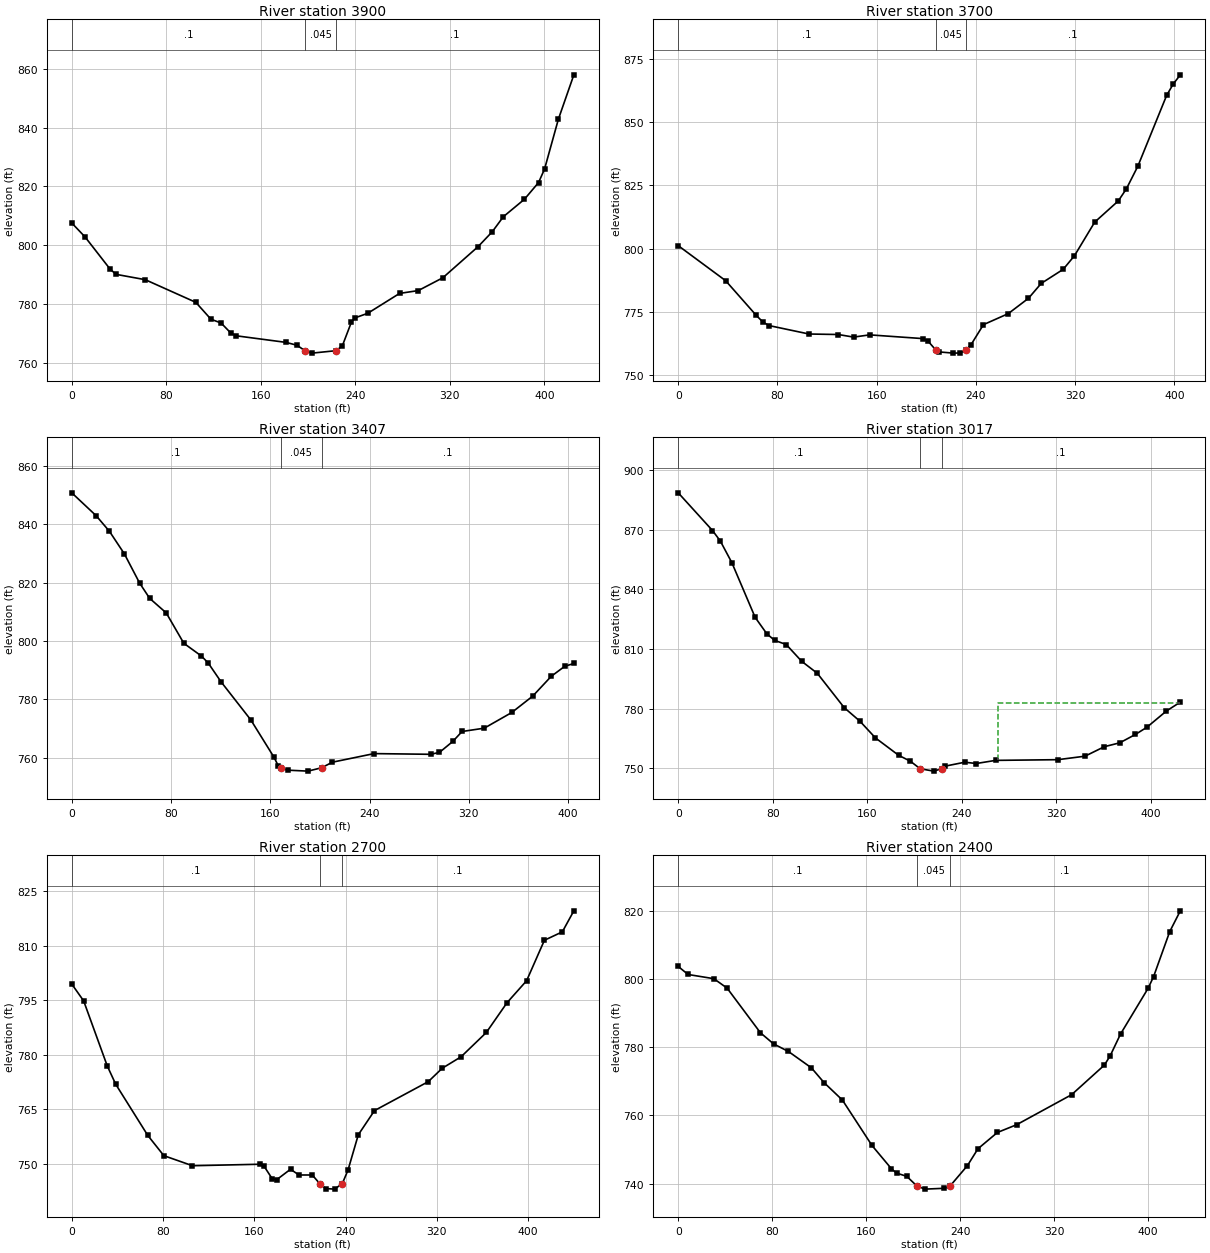
Type RM Length L Ch R = 1 ,3900    ,197.5,200.1,201.7
XS GIS Cut Line= 6
  1636785.228266469788.9629508411636729.04333901469856.040900677
1636680.88464268469913.5365205851636616.67282884469990.197128415
 1636568.5141325470047.6927483381636512.32920551470114.771026254
#Sta/Elev= 30
       0  807.55    11.3  802.77    32.3  791.92    37.4  790.07    62.2  788.25
     105  780.54   117.8  774.79   126.4   773.5   134.7  770.06   139.2  769.15
   181.3  766.91   190.6  765.94  197.33764.0927   203.4  763.25  223.92764.0925
   229.1  765.81   236.7  773.79   239.5  775.22   250.5   776.8   277.5  783.58
   293.3  784.54   314.1   788.9     344  799.52     356   804.6   365.3  809.67
   383.2  815.64   395.1   821.3   400.2   825.9   411.9  842.86     425  857.98
#Mann= 3 ,-1,0
       0      .1       0  197.33    .045       0  223.92      .1       0
Bank Sta=197.33,223.92
XS Rating Curve= 0 ,0
Exp/Cntr(USF)=0,0
Exp/Cntr=0.3,0.1

Type RM Length L Ch R = 1 ,3700    ,285.5,292.6,298.2
XS GIS Cut Line= 3
1636662.44502286469684.518030343 1636464.8299458469851.371479404
1636356.71814505469949.662490859
#Sta/Elev= 30
       0  801.13    38.2   787.3    62.9  773.59    68.1  771.04    73.1  769.58
   105.4  766.24     129  766.04   141.3  765.02   154.3   765.9   197.1  764.43
   201.4   763.4  207.68759.8903   210.4  759.16   221.8  758.69   227.1  758.75
  231.88759.8916   235.8  761.85     246  769.93     266  774.28   282.3  780.34
   292.6  786.23   310.3  791.78   319.4  797.17   335.7  810.42   354.7  818.79
   361.2  823.54   370.5  832.53   393.7  860.49     399  864.96   404.7  868.59
#Mann= 3 ,-1,0
       0      .1       0  207.68    .045       0  231.88      .1       0
Bank Sta=207.68,231.88
XS Rating Curve= 0 ,0
Exp/Cntr(USF)=0,0
Exp/Cntr=0.3,0.1

Type RM Length L Ch R = 1 ,3407    ,408.7,390.2,370.6
XS GIS Cut Line= 4
1636554.62947141469468.9982080361636427.07599679469552.340288759
1636337.96119923469572.1579632991636271.33908874469718.666270802
#Sta/Elev= 30
       0  850.82    19.7  842.95    30.4  837.59    42.4  829.88    54.7  819.85
    62.8  814.62    76.1  809.65    90.3  799.22   104.5  794.84   109.9  792.49
   120.3  786.01   144.3  772.94     163  760.12   166.3   757.3  168.29 756.544
   173.9  755.71   190.4  755.38   201.4756.5455     210  758.44   243.6  761.39
   289.1  761.15   296.3   761.8   307.1  765.58   314.5  768.97   332.4  770.11
   354.6  775.49   371.5  781.12   386.4   787.9   397.3  791.34   404.6  792.29
#Mann= 3 ,-1,0
       0      .1       0  168.29    .045       0   201.4      .1       0
Bank Sta=168.29,201.4
XS Rating Curve= 0 ,0
Exp/Cntr(USF)=0,0
Exp/Cntr=0.3,0.1

Type RM Length L Ch R = 1 ,3017    ,311.5,317.3,322.2
XS GIS Cut Line= 6
1636075.20564507469184.3126770971636071.40512774 469271.73015317
1636068.14726024469346.6594652651636063.80376499469446.564777267
1636060.54655366469521.494089347 1636056.7466925 469608.91156542
#Sta/Elev= 30
       0  888.43      29   869.5    35.6  864.25    45.4  853.34    65.1  825.89
      75  817.63    81.6  814.33    91.4  812.25   104.5  803.82   117.7   797.8
   140.5  780.53   153.8  773.74   166.9  765.36   186.6   756.6   196.5  753.64
  204.75  749.87   216.2  748.66  223.13749.8723     226  751.17   242.5  753.13
   252.3  752.49   268.7  754.06   321.3  754.41   344.3  756.16   360.7  760.93
   373.8  762.89     387  767.08   396.8  770.73   413.2  778.84     425  783.32
#Mann= 3 ,-1,0
       0      .1       0  204.75    .045       0  223.13      .1       0
#XS Ineff= 2 , 0
                          271.06          782.84
Permanent Ineff=
       F       F
Bank Sta=204.75,223.13
XS Rating Curve= 0 ,0
Exp/Cntr(USF)=0,0
Exp/Cntr=0.3,0.1

Type RM Length L Ch R = 1 ,2700    ,294.3,299.8,304.4
XS GIS Cut Line= 6
1635853.51031317469200.3627500831635818.91983117469289.898332179
1635781.77226767469362.4769271761635727.56469892469446.511207923
1635686.63892776469509.3608197571635638.89230409469582.685476258
#Sta/Elev= 30
       0  799.51    10.4  794.89    31.1  776.97    38.5  771.94    66.6  757.85
    80.7  752.27   105.8   749.5   164.7  749.91   168.4  749.42   175.8  745.85
   179.6  745.66   191.7  748.53   199.1  746.95   210.8  746.95  217.29744.5737
   222.6  743.22   230.3  743.06  237.08 744.572   242.1  748.32   251.1  758.02
   265.3  764.68   312.4  772.64   324.6  776.32   341.2   779.5   363.3  786.18
   381.5   794.4   398.6  800.43   414.2  811.57   429.9  813.88     440  819.67
#Mann= 3 ,-1,0
       0      .1       0  217.29    .045       0  237.08      .1       0
Bank Sta=217.29,237.08
XS Rating Curve= 0 ,0
Exp/Cntr(USF)=0,0
Exp/Cntr=0.3,0.1

Type RM Length L Ch R = 1 ,2400    ,303.6,300,289.7
XS GIS Cut Line= 6
1635726.93018575469079.5158789161635653.48807542469127.082056761
 1635590.5380701469167.8529725821635506.60451092469222.214412421
 1635446.5993816469267.5328913331635383.59622675 469331.21616292
#Sta/Elev= 30
       0  803.64     8.4  801.29    30.3  800.06    41.6  797.29      70  784.19
    81.1  780.96    93.8  778.72   113.3  773.94   124.1   769.6   139.7  764.49
   164.9  751.17   181.5  744.33   185.8  743.08   194.5  742.13  203.09 739.302
     210  738.38   226.6  738.63  231.37739.3023   246.1  745.26   255.1  750.22
   271.6  754.98     288  757.26   334.8  766.06   362.7  774.74   367.6  777.45
   376.4  783.82   399.8  797.19   404.5  800.62   418.3  813.86   427.3  819.95
#Mann= 3 ,-1,0
       0      .1       0  203.09    .045       0  231.37      .1       0
Bank Sta=203.09,231.37
XS Rating Curve= 0 ,0
Exp/Cntr(USF)=0,0
Exp/Cntr=0.3,0.1

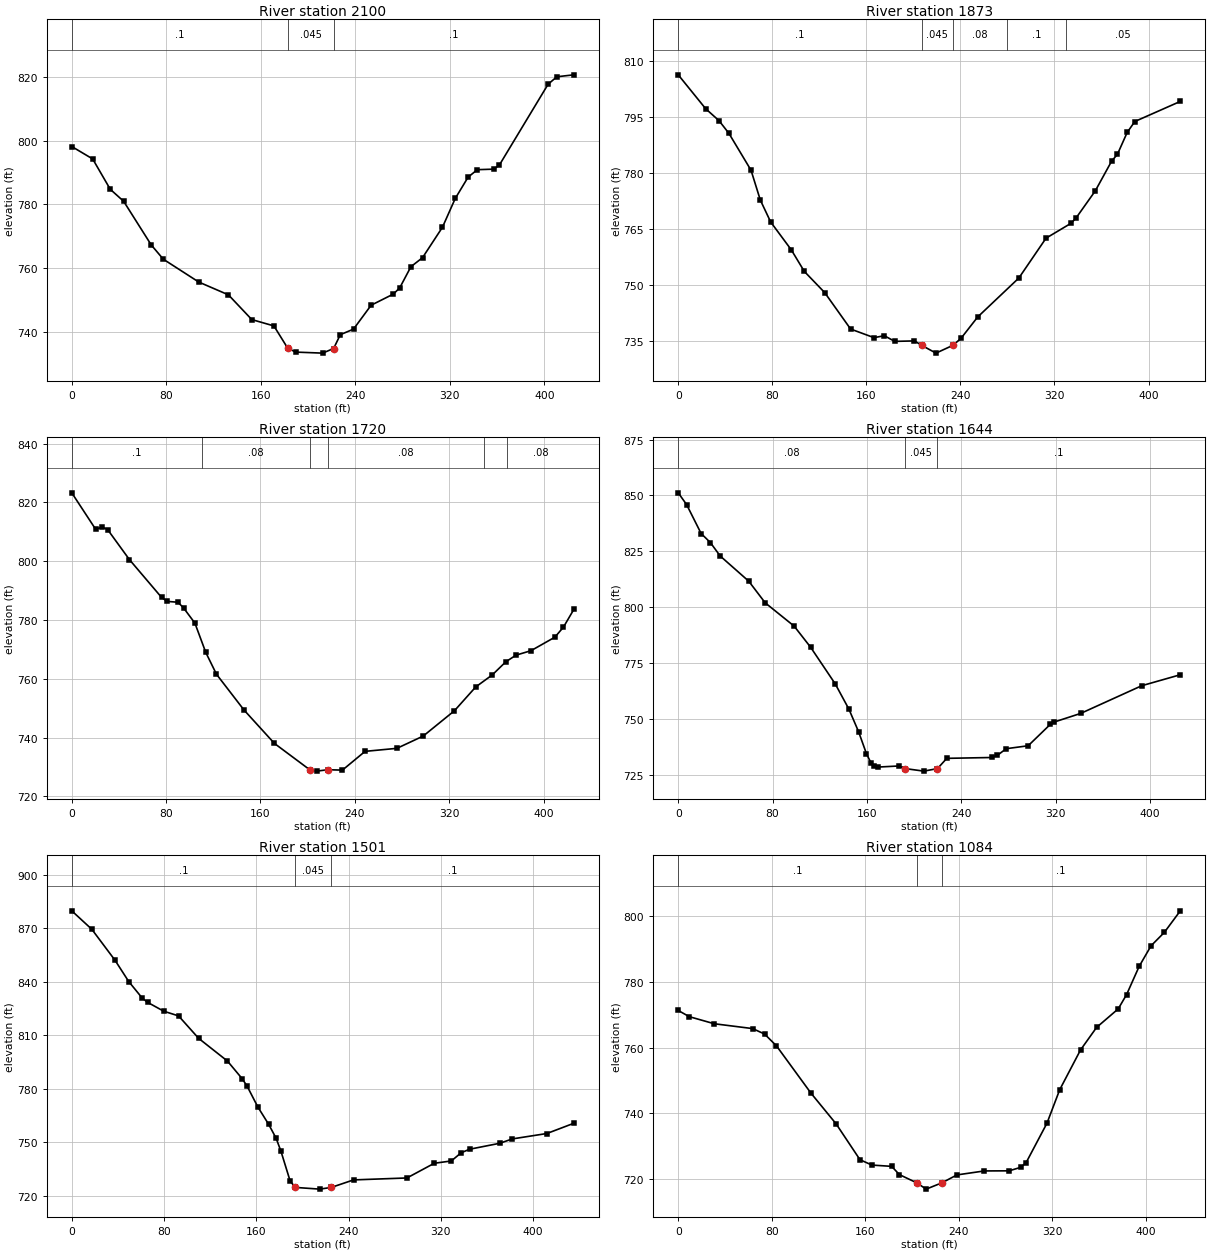
Type RM Length L Ch R = 1 ,2100    ,221.2,227,230.9
XS GIS Cut Line= 6
1635393.62540618468866.4615150091635351.51394184468943.161164761
 1635315.4182135469008.9041435121635267.29068509469096.560792342
1635231.19495675   469162.3034431635189.08316433469239.003420845
#Sta/Elev= 30
       0  798.13    17.7  794.22    32.6  784.68    43.9  780.93    67.3  767.19
    77.5  762.72   107.5  755.55   132.6  751.53   152.4  743.76   171.1  741.77
  182.95734.6755   189.8  733.54   212.3  733.22  221.67734.6729   227.3  739.01
   238.5  740.76   253.4  748.27   272.2  751.77   277.6  753.72   287.1  760.38
   296.9   763.2   313.8  772.78   324.6   781.8   335.5  788.51   343.3  790.85
   357.3  791.02     362  792.33   403.2  817.69   410.6  820.04     425  820.65
#Mann= 3 ,-1,0
       0      .1       0  182.95    .045       0  221.67      .1       0
Bank Sta=182.95,221.67
XS Rating Curve= 0 ,0
Exp/Cntr(USF)=0,0
Exp/Cntr=0.3,0.1

Type RM Length L Ch R = 1 ,1873    ,151.9,153.4,155.3
XS GIS Cut Line= 2
1635271.37474792 468777.84359771 1634952.5109112469061.870917696
#Sta/Elev= 30
       0   806.3    23.3  797.22    34.7     794    43.1   790.6    61.9  780.71
    69.8  772.72    78.6  766.84    96.2  759.34   107.2  753.59   124.6  747.88
   146.6  738.12   166.5  735.81   175.3  736.33   184.1  734.81   200.9  734.94
  207.13733.7398   219.2  731.66  233.53733.7407   240.4  735.59   254.7  741.36
   289.7  751.81   312.8  762.49   334.1  766.49   338.4  767.93   354.7  775.18
   368.6  783.16   373.5  784.97   381.8  790.84   388.3  793.78     427  799.17
#Mann= 5 ,-1,0
       0      .1       0  207.13    .045       0  233.53     .08       0
     280      .1       0     330     .05       0
Bank Sta=207.13,233.53
XS Rating Curve= 0 ,0
Exp/Cntr(USF)=0,0
Exp/Cntr=0.3,0.1

Type RM Length L Ch R = 1 ,1720    ,75.1,75.5,76.2
XS GIS Cut Line= 4
 1635167.8931765 468663.531679211635054.33831134468777.867476186
1634945.29686315468844.9292273861634862.89933279468953.767756292
#Sta/Elev= 30
       0  823.29    20.3  810.85    25.8  811.66    30.4  810.78    48.9  800.55
    76.1  787.71    80.8  786.34    90.1  786.04    94.8  784.11   104.4  778.94
   113.6  768.98   122.7  761.53     146  749.38   171.8     738  201.77  729.03
   207.6  728.56   217.1  729.03   229.5  728.91   248.7  735.29   275.7  736.32
     298   740.5   324.5  749.13   342.5  757.21   356.6  761.33     368  765.77
   376.7  768.04   389.4  769.56   409.6  774.15   416.9  777.58   425.7  783.62
#Mann= 6 ,-1,0
       0      .1       0     110     .08       0  201.77    .045       0
   217.1     .08       0  349.16      .1       0  369.16     .08       0
Bank Sta=201.77,217.1
XS Rating Curve= 0 ,0
Exp/Cntr(USF)=0,0
Exp/Cntr=0.3,0.1

Type RM Length L Ch R = 1 ,1644    ,148.4,143.4,138.3
XS GIS Cut Line= 4
 1635120.2649247468604.6277222731635006.71005954468718.963519249
1634897.66861135468786.0252704491634815.27108099468894.863799355
#Sta/Elev= 30
       0  851.16     7.1  845.89    19.4  832.96    27.2  828.93    35.6  822.88
    59.8  811.61    73.7  801.96    98.3   791.5   112.2   782.1   133.1  765.68
   144.7  754.37   152.9  744.29   159.6   734.4   163.3  730.45   165.9  728.99
   169.7  728.46   187.1  728.93  192.52  727.76   208.2  726.63   219.8  727.76
   227.7  732.35   265.8  732.73   270.6   733.7   278.1  736.67   296.7  737.98
   315.4  747.52   318.9  748.62   341.2  752.45     393  764.85   425.7  769.76
#Mann= 3 ,-1,0
       0     .08       0  192.52    .045       0   219.8      .1       0
Bank Sta=192.52,219.8
XS Rating Curve= 0 ,0
Exp/Cntr(USF)=0,0
Exp/Cntr=0.3,0.1

Type RM Length L Ch R = 1 ,1501    ,425.2,416.7,406
XS GIS Cut Line= 6
1635007.17079851468472.3766732511634951.76211667468540.097666427
1634904.26910143468598.1444663411634841.92244133468676.339519918
1634806.96024093468747.0040767491634765.44293551468831.336257175
#Sta/Elev= 30
       0  879.67    17.4   869.3    37.5  851.95    49.4  840.01    61.1  830.74
    65.7  828.37    79.7   823.4    92.6  820.75     110  808.17     135  795.42
   147.7  785.57     152  781.39   161.3  769.72   170.7  759.97   177.2  752.12
   181.4  744.79   189.3  728.22  193.81724.5892     215  723.63  225.02724.5905
   244.3   728.8   290.6  729.89   314.3  738.13   329.1  739.43   337.6  744.02
   344.9     746   371.1  749.34     382  751.79   411.9  754.81   435.3  760.56
#Mann= 3 ,-1,0
       0      .1       0  193.81    .045       0  225.02      .1       0
Bank Sta=193.81,225.02
XS Rating Curve= 0 ,0
Exp/Cntr(USF)=0,0
Exp/Cntr=0.3,0.1

Type RM Length L Ch R = 1 ,1084    ,75.8,73.9,71.7
XS GIS Cut Line= 4
1634523.15074894468344.899616108  1634475.883468 468517.70257856
1634475.28089774468594.0572093631634405.96397543468753.424061523
#Sta/Elev= 30
       0  771.27     9.4  769.39    30.8  767.23    63.6  765.76    73.8  764.11
      84  760.51   113.6  746.09     135   736.8   155.4  725.91   165.6  724.28
   182.5  723.89   189.1  721.38  203.87 718.899     212  716.97  225.53718.8998
   238.3  721.29   261.8   722.5   282.9  722.53   292.9   723.6   297.5  725.05
   315.3  737.02   326.2   747.2     344  759.28   357.7  766.11   376.2  771.75
   383.4  776.12   394.1  784.66   404.3  790.93   415.6  794.98   429.3  801.55
#Mann= 3 ,-1,0
       0      .1       0  203.87    .045       0  225.53      .1       0
Bank Sta=203.87,225.53
XS Rating Curve= 0 ,0
Exp/Cntr(USF)=0,0
Exp/Cntr=0.3,0.1

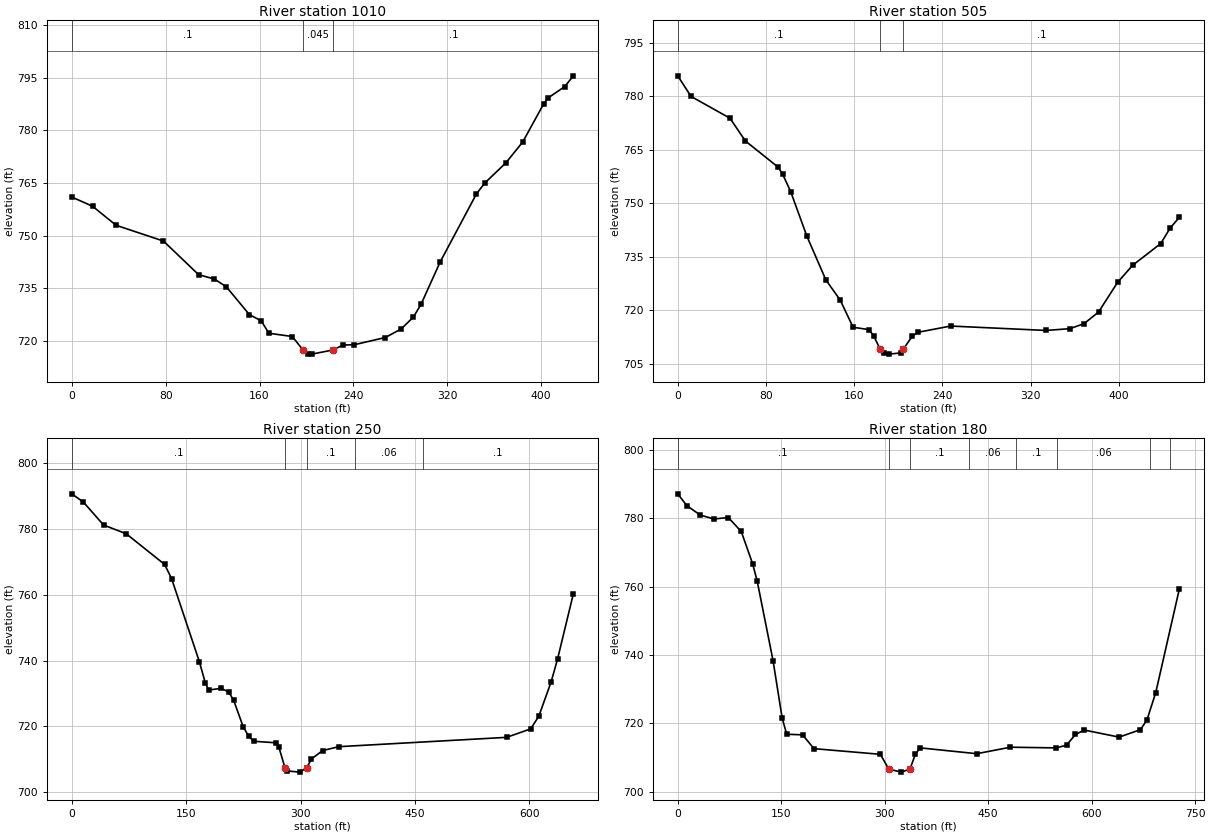
Type RM Length L Ch R = 1 ,1010    ,495.6,505,514.6
XS GIS Cut Line= 5
  1634435.048567468329.8950551281634416.40129457468415.407023204
 1634400.7326277468508.9530731121634412.10392399468607.253391109
 1634353.6162234 468741.12679139
#Sta/Elev= 30
       0  761.03    17.7   758.4    37.8  752.97    78.1  748.48   108.1  738.89
   121.5  737.65   131.7  735.44   151.4  727.49   161.4  725.75     168  722.19
   187.9  721.26  197.03717.4396   201.2  716.32   204.5  716.24  222.79717.4379
   230.9  718.82   240.8  718.93   267.2  720.98   280.6   723.4   291.1   726.8
   297.6  730.45     314  742.58   344.8  761.91   351.9  765.02   369.8  770.74
   384.2   776.7   402.1  787.59   405.7  789.24     420  792.51   427.4  795.58
#Mann= 3 ,-1,0
       0      .1       0  197.03    .045       0  222.79      .1       0
Bank Sta=197.03,222.79
XS Rating Curve= 0 ,0
Exp/Cntr(USF)=0,0
Exp/Cntr=0.3,0.1

Type RM Length L Ch R = 1 ,505     ,257.7,255.1,245.6
XS GIS Cut Line= 2
 1634131.3577006468124.2276014911633833.90952131468468.233101722
#Sta/Elev= 30
       0  785.68    12.1  779.91    47.4  773.81    61.3  767.46    90.9  760.14
    95.2  758.11   102.4  753.27   117.1  740.79   134.3  728.56   147.3  722.92
     159   715.3   173.3  714.65   177.6  712.94  183.43709.2331   186.9  708.07
   191.6  707.78   202.7  708.13  204.69709.2338   212.7  712.83   217.8  713.89
   247.4  715.64   333.8  714.41   355.4   714.9   368.4  716.31   381.5  719.55
   398.8  727.87   412.5  732.66   437.9  738.73   446.5  743.08   454.8  746.08
#Mann= 3 ,-1,0
       0      .1       0  183.43    .045       0  204.69      .1       0
Bank Sta=183.43,204.69
XS Rating Curve= 0 ,0
Exp/Cntr(USF)=0,0
Exp/Cntr=0.3,0.1

Type RM Length L Ch R = 1 ,250     ,67.5,70.3,67.2
XS GIS Cut Line= 6
 1633977.8793424468007.2720148821633803.94860486468027.892312819
1633799.02934932468119.5134473221633755.37095637468266.476206691
1633717.86163285468363.0165967381633766.63765279468487.866638133
#Sta/Elev= 30
       0  790.76    15.3  788.24    41.7  781.27    71.5   778.6   121.8  769.27
   130.9  764.98   167.3  739.72   175.1  733.24   179.5  731.06   195.9  731.57
   205.8  730.46   212.4  727.89   224.8  719.89     232  716.99   238.6  715.47
   268.2     715   271.7  713.64  279.53707.4542   281.9  706.46     299  706.08
  308.29707.4536   314.3  710.09   328.9  712.63     350  713.82   570.2  716.66
   601.8  719.24   612.4  723.06   628.6  733.51   637.1  740.54   657.8  760.38
#Mann= 5 ,-1,0
       0      .1       0  279.53    .045       0  308.29      .1       0
  371.69     .06       0  460.21      .1       0
Bank Sta=279.53,308.29
XS Rating Curve= 0 ,0
Exp/Cntr(USF)=0,0
Exp/Cntr=0.3,0.1

Type RM Length L Ch R = 1 ,180     ,0,0,0
XS GIS Cut Line= 6
1633946.16767117 467988.672588171633741.49158649468006.833258335
1633736.57233094468098.4543928371633692.91393799468245.417152207
1633655.40461447468341.9575422531633734.92598156468495.708209968
#Sta/Elev= 30
       0  787.12    13.1  783.67    32.8  780.89    52.6  779.76    73.3  780.19
    92.1   776.1   108.6  766.65   115.2  761.59   138.2  738.31   151.4  721.49
     158  716.78     181  716.61   197.5  712.57   293.8  710.91  305.83706.6012
     324   705.7  336.73706.6013   344.4  710.88   351.3   712.8   433.5  711.09
   482.3  712.99   548.9  712.79   563.7   713.6   576.6  716.73   589.5  718.01
   639.9  715.94   670.8  718.13   680.2  720.95     693  728.99   727.2   759.3
#Mann= 8 ,-1,0
       0      .1       0  305.83    .045       0  336.73      .1       0
  422.02     .06       0  490.54      .1       0  550.54     .06       0
  684.12      .1       0  714.12     .06       0
Bank Sta=305.83,336.73
XS Rating Curve= 0 ,0
Exp/Cntr(USF)=0,0
Exp/Cntr=0.3,0.1
LCMann Table=0

Chan Stop Cuts=-1
Use User Specified Reach Order=0
Composite Channel Slope=5